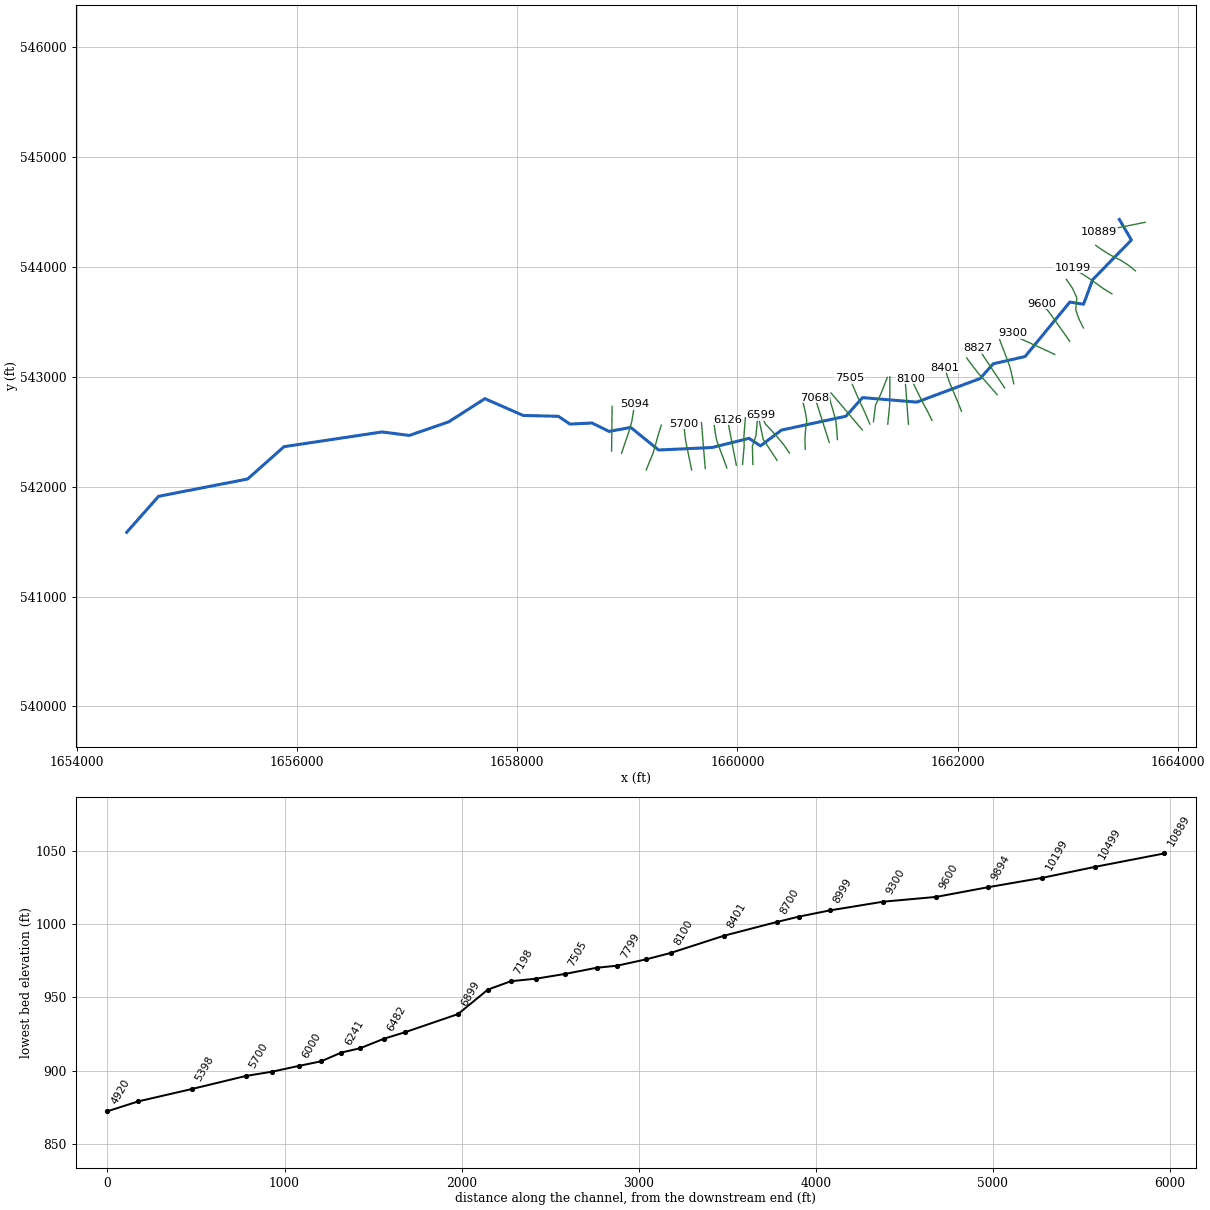
--- BruceRn.prj (project) ---

Proj Title=BruceRn
Current Plan=p01
Default Exp/Contr=0,0
English Units
Geom File=g01
Flow File=f01
Plan File=p01
BEGIN DESCRIPTION:
---------- MODELED AS PART OF WVEM CTP PROGRAM, 2025----------
Stream Name: Bruce Run
Flood Zone: AFH
Marshall County, WV
HEC-RAS Version: RAS 6.6
Vertical Datum: NAVD88
Projection: NAD 1983 StatePlane West Virginia N FIPS 4701 (US Feet)
Terrain: 1-meter West Virginia FEMA R3 South Central (collected 2018-2019)
Land Use: 2024 NLCD
Hydrologic Method:
Duda et al., "Estimation of magnitude and frequency of floods for rural, unregulated streams in and near Virginia and West Virginia." September 8, 2025.
Additional Model Notes:
None
END DESCRIPTION:
DSS File=dss
DSS Export Rating Curves= 0
DSS Export Rating Curve Sorted= 0
DSS Export Volume Flow Curves= 0
DXF OffsetX= 0
DXF OffsetY= 0
DXF ScaleX= 0
DXF ScaleY= 0

--- BruceRn.p01 (plan) ---

Plan Title=Floodplain
Program Version=6.60
Short Identifier=Floodplain
Geom File=g01
Flow File=f01
Subcritical Flow
K Sum by GR= 0
Std Step Tol= 0.01
Critical Tol= 0.01
Num of Std Step Trials= 20
Max Error Tol= 0.3
Flow Tol Ratio= 0.001
Split Flow NTrial= 30
Split Flow Tol= 0.02
Split Flow Ratio= 0.02
Log Output Level= 0
Friction Slope Method= 1
Unsteady Friction Slope Method= 2
Unsteady Bridges Friction Slope Method= 1
Parabolic Critical Depth
Global Vel Dist= 0 , 0 , 0
Global Log Level= 0
CheckData=False
Encroach Param=-1 ,0,0, 0
Flow Ratio Tolerance=0.1
Flow Ratio Min Ratio=0.5
Flow Ratio Max Ratio=4
Flow Ratio Max Iterations= 10
Computation Interval=0.1SEC
Output Interval=1SEC
Instantaneous Interval=Max Profile
Mapping Interval=1HOUR
Computation Time Step Use Courant=        0
Computation Time Step Use Time Series=    0
Computation Time Step Count To Double=0
Computation Time Step Max Doubling=0
Computation Time Step Max Halving=0
Computation Time Step Residence Courant=0
Run HTab= 0
Run UNet= 0
Run Sediment= 0
Run PostProcess= 0
Run WQNet= 0
Run RASMapper=-1
UNET Theta= 0
UNET Theta Warmup= 0
UNET ZTol= 0
UNET ZSATol= 0
UNET MxIter= 0
UNET Max Iter WO Improvement= 0
UNET MaxInSteps= 0
UNET DtIC= 0
UNET DtMin= 0
UNET MaxCRTS= 0
UNET WFStab= 0
UNET SFStab= 0
UNET WFX= 1
UNET SFX= 1
UNET Gravity=32.17405
UNET 1D Methodology=Finite Difference
UNET DSS MLevel= 1
UNET Pardiso=0
UNET DZMax Abort= 0
UNET Use Existing IB Tables= 0
UNET Froude Reduction=False
UNET Froude Limit= 0
UNET Froude Power= 0
UNET D1 Cores= 0
UNET WindReference=Eulerian
UNET WindDragFormulation=Hsu (1988)
UNET D2 Coriolis=0
UNET D2 Cores= 0
UNET D2 Theta= 1
UNET D2 Theta Warmup= 1
UNET D2 Z Tol= 0.01
UNET D2 Volume Tol= 0.01
UNET D2 Max Iterations= 20
UNET D2 Advanced Convergence=0
UNET D2 WS Max Tol=0.15
UNET D2 WS RMS Tol=0.002
UNET D2 WS Stall Tol=1
UNET D2 Equation= 0
UNET D2 RampUpFraction=0.1
UNET D2 TimeSlices= 1
UNET D2 Turbulence Formulation=Non-Conservative (original)
UNET D2 Eddy Viscosity=0.3
UNET D2 Transverse Eddy Viscosity=0.1
UNET D2 Smagorinsky Mixing=0
UNET D2 BCVolumeCheck=0
UNET D2 Cores=0
UNET D2 SolverType=PARDISO (Direct)
UNET D2 Minimum Iterations= 3
UNET D2 Maximum Iterations= 30
UNET D2 Restart Number= 10
UNET D2 Relaxation Coeff=1.3
UNET D2 SOR Precondition Iterations= 10
UNET D2 ILUT Maximum Fill= 8
UNET D2 ILUT Tolerance=1E-08
UNET D2 Convergence Tolerance=0.00001
PS Theta= 1
PS WS Tol= 0.01
PS Volume Tol= 0.01
PS Max Iterations= 20
PS Equation= 0
PS Advance Time Step=-1
PS Target Courant=0.9
PS Time Slices= 1
PS Iterate With 2D=0
PS Project Initial WSE from DS=-1
PS Ramp Up Initial WSE from US=-1
PS Cores=0
UNET D1D2 MaxIter= 0
UNET D1D2 ZTol=0.01
UNET D1D2 QTol=0.1
UNET D1D2 MinQTol=1
DSS File=dss
Write IC File= 0
Write IC File at Fixed DateTime=0
Write IC File at Sim End=0
Echo Input=False
Echo Parameters=False
Echo Output=False
Write Detailed= 0
HDF Write Warmup=0
HDF Write Time Slices=0
HDF Flush=0
HDF Compression= 1
HDF Chunk Size= 1
HDF Spatial Parts= 1
HDF Use Max Rows=0
HDF Fixed Rows= 1
Calibration Method= 0
Calibration Iterations= 20
Calibration Max Change=0.05
Calibration Tolerance=0.2
Calibration Maximum=1.5
Calibration Minimum=0.5
Calibration Optimization Method= 1
WQ AD Non Conservative
WQ ULTIMATE=-1
WQ Max Comp Step=1HOUR
WQ Output Interval=15MIN
WQ Output Selected Increments= 0
WQ Create Restart=0
WQ Fixed Restart=0
WQ System Summary=0
WQ Write To DSS=0
Sorting and Armoring Iterations= 10
XS Update Threshold= 0.02
Bed Roughness Predictor= 0
Processes Affected by Predictor=Sediment Only
Hydraulics Update Threshold= 0.02
Energy Slope Method= 1
Volume Change Method= 1
Sediment Retention Method= 0
Sediment TS Multiplier= 1
Warm Up Method= 0
XS Weighting Method= 0
Number of US Weighted Cross Sections= 1
Number of DS Weighted Cross Sections= 1
Upstream XS Weight=0
Main XS Weight=1
Downstream XS Weight=0
Number of DS XS's Weighted with US Boundary= 1
Upstream Boundary Weight= 1
Weight of XSs Associated with US Boundary= 0
Number of US XS's Weighted with DS Boundary= 1
Downstream Boundary Weight= 0.5
Weight of XSs Associated with DS Boundary= 0.5
Percentile Method= 0
Sediment Output Level= 3
Mass or Volume Output= 0
Output Increment Type= 1
Profile and TS Output Increment= 1
Transport Output Increment 1
XS Output Flag= 0
XS Output Increment= 10
Read HDF5 Sediment Hotstart= 0
Sediment Hotstart Type= 0
Write Gradation File= 0
Read Gradation Hotstart= 0
Write HDF5 File= 1
Write Binary Output= 1
Write DSS Sediment File= 0
DSS Sediment Output Type= 1
SV Curve= 0
Specific Gage Flag= 0
Subcell Erosion Methods= 0
Subcell Deposition Methods= 0
Advection Scheme= 1
Matrix Solver= 0
Implicit Weighting Factor= 1
Maximum Outer Loop Convergence Iterations= 5
Convergence Maximum Absolute= 0.001
Convergence RMSE= 0.0001
Grain Fractions Max Abs Error= 0.001
Max Subgrid Regions= 1
Max Subgrid Length Scale= 3.402823E+38
Initial Layer Thickness= 3
Min Layer Thickness= 0.1
Max Layer Thickness= 6
Number of Layers= 5

--- BruceRn.f01 (steady flow) ---

Flow Title=Flow
Program Version=6.60
Number of Profiles= 1
Profile Names=P100yr
River Rch & RM=BruceRn,Main            ,10889
     750
River Rch & RM=BruceRn,Main            ,7799
     882
River Rch & RM=BruceRn,Main            ,3899
    1210
Boundary for River Rch & Prof#=BruceRn,Main            , 1
Up Type= 0
Dn Type= 3
Dn Slope=0.02781
DSS Import GetInterval= 0
DSS Import GetPeak= 0
DSS Import FillOption= 0

--- BruceRn.g01 (geometry) ---

Geom Title=Geometry
Program Version=6.60

River Reach=BruceRn         ,Main
Reach XY= 30
     1663466.797       544433.56     1663576.162       544246.29
     1663224.557      543884.973     1663141.998      543661.577
     1663017.369      543681.143     1662611.094      543185.454
     1662321.755      543119.367     1662202.917      542985.361
     1661628.121      542770.529     1661135.286      542811.471
     1660984.219       542642.17     1660399.279      542515.913
     1660208.775      542372.373      1660104.84         542441.
     1659769.164      542357.454     1659283.864      542334.609
      1659031.33      542539.744     1658834.742      542504.001
     1658679.337       542580.15     1658478.087      542570.825
     1658373.965      542641.535      1658053.83      542649.305
     1657706.872      542802.037     1657378.576      542591.166
     1657020.574      542467.207     1656772.884      542499.074
      1655882.73      542364.913      1655552.58      542070.679
      1654743.92      541913.162     1654454.819      541585.691

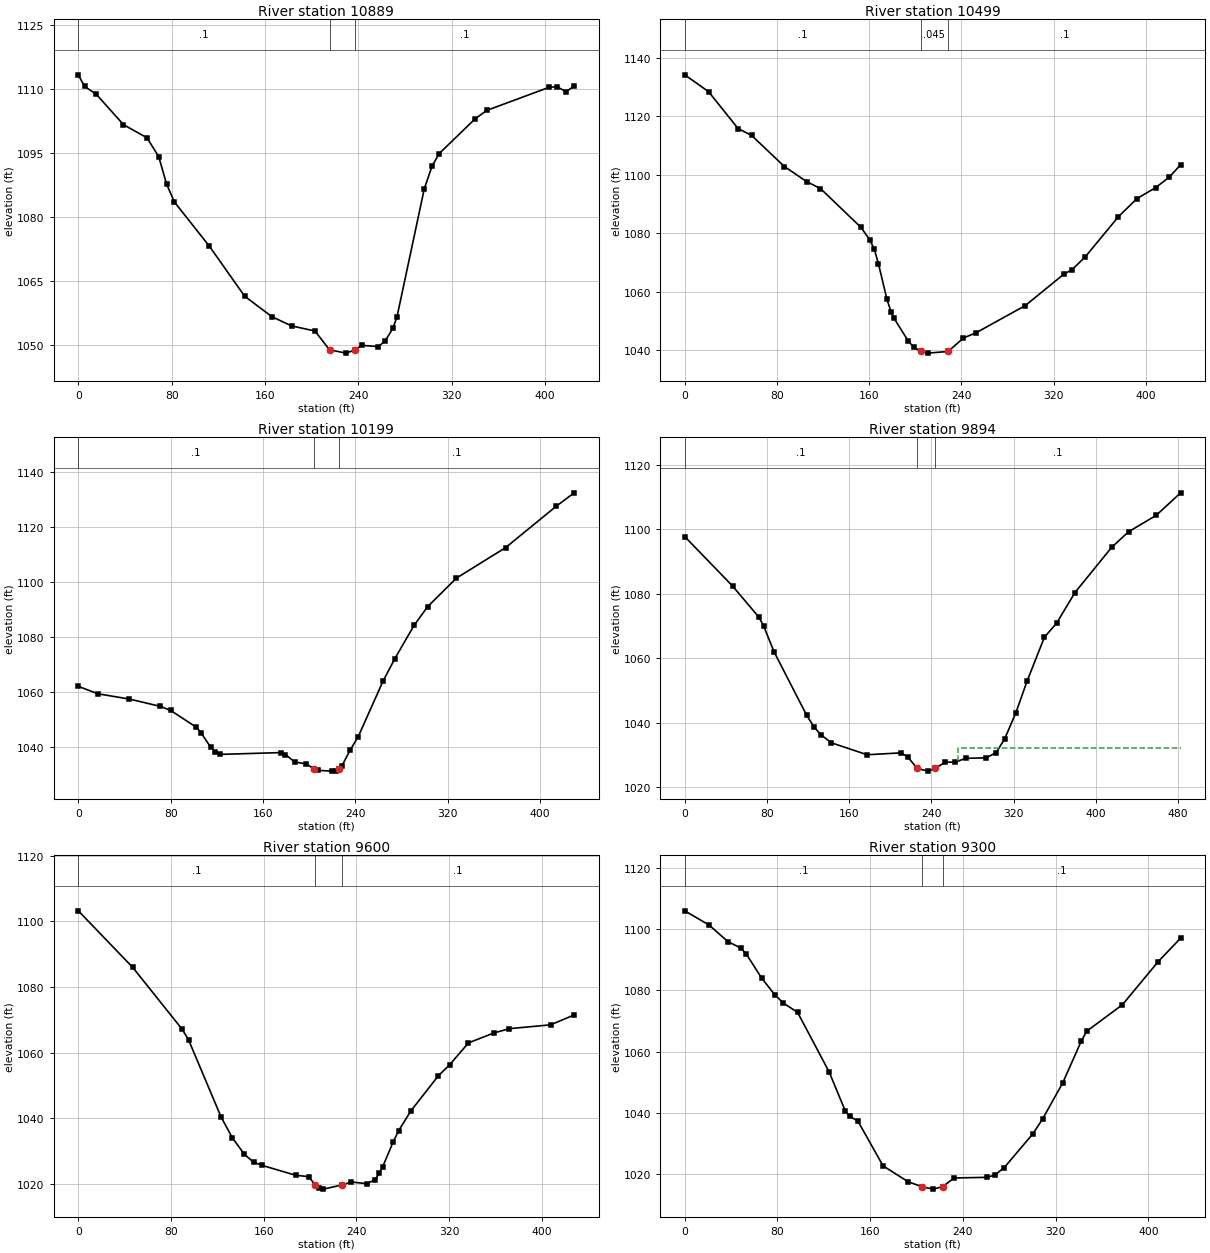
Type RM Length L Ch R = 1 ,10889   ,392.9,390.5,376.4
XS GIS Cut Line= 2
1663701.74523868544407.6529585061663285.29672402544323.513360646
#Sta/Elev= 30
       0 1113.29     5.3 1110.57    15.3 1108.76    38.7  1101.6    58.8 1098.54
    68.9 1094.12    75.6 1087.69    82.3 1083.49   112.4 1073.08   142.5  1061.4
   165.9 1056.59   182.7 1054.44   202.8 1053.23  215.251048.831   229.5 1048.05
  237.181048.832   242.9 1049.88   257.1 1049.57     263 1050.93   269.7 1053.93
   273.1 1056.59   296.5 1086.62   303.2 1091.94   309.3 1094.84     340 1102.97
     350 1104.95   403.6 1110.38   410.3  1110.5   417.9 1109.34   424.9 1110.64
#Mann= 3 ,-1,0
       0      .1       0  215.25    .045       0  237.18      .1       0
Bank Sta=215.25,237.18
XS Rating Curve= 0 ,0
Exp/Cntr(USF)=0,0
Exp/Cntr=0.3,0.1

Type RM Length L Ch R = 1 ,10499   ,300.5,300.4,297
XS GIS Cut Line= 6
1663613.01352109543965.3759494271663544.11831768544020.806612834
1663480.64731601544061.1270702631663391.16094643544106.987542838
1663325.34382084544146.3066899181663252.29147351544197.577912837
#Sta/Elev= 30
       0 1134.25    20.6 1128.49    46.2 1115.86    57.9 1113.51    86.4 1102.84
     106  1097.6   117.7 1095.29   152.7 1082.04   160.5 1077.71   164.4 1074.49
     168 1069.48   175.4 1057.29     179 1052.96   181.4 1050.93   193.8 1043.07
   198.4 1041.03  204.571039.478   210.6 1038.92  228.351039.478   241.7 1044.09
   252.8 1045.93   295.4 1055.22   328.8 1065.97     336 1067.52   347.4 1071.91
   376.1 1085.64   392.3 1091.87   408.4  1095.6   420.4 1099.24   430.1 1103.46
#Mann= 3 ,-1,0
       0      .1       0  204.57    .045       0  228.35      .1       0
Bank Sta=204.57,228.35
XS Rating Curve= 0 ,0
Exp/Cntr(USF)=0,0
Exp/Cntr=0.3,0.1

Type RM Length L Ch R = 1 ,10199   ,309.2,304.1,295.9
XS GIS Cut Line= 6
1663399.36368592543756.1266960051663321.97768584543803.593792677
1663260.64119434543848.7711957541663178.44811726543905.802577749
1663115.62704867543946.771984011 1663042.3355286543994.569788679
#Sta/Elev= 30
       0 1062.16      17 1059.46    44.1 1057.56    70.9 1054.91    79.9 1053.43
   102.3  1047.3   106.4 1045.23   114.5 1040.14   118.6 1038.42   122.7 1037.46
   175.5 1038.11   179.4 1037.41   187.4 1034.69   197.5 1034.01  203.941032.209
   207.4 1031.67   219.4 1031.38   223.5 1031.55  226.141032.207   228.2 1033.16
   235.3 1038.91   242.3 1043.76   263.8 1063.93     274  1072.1   290.8 1084.29
   302.5 1091.07   327.5 1101.46   370.2 1112.57   413.8 1127.51   429.5 1132.44
#Mann= 3 ,-1,0
       0      .1       0  203.94    .045       0  226.14      .1       0
Bank Sta=203.94,226.14
XS Rating Curve= 0 ,0
Exp/Cntr(USF)=0,0
Exp/Cntr=0.3,0.1

Type RM Length L Ch R = 1 ,9894    ,288.9,294.3,294.8
XS GIS Cut Line= 6
1663140.67621118 543445.598117591663097.69007668543532.484754846
1663070.85581276543611.8307247611663080.93125193543720.426964253
1663042.76400542543803.9205636681662986.42914434543887.597233593
#Sta/Elev= 30
       0 1097.77    46.6  1082.4    72.2 1072.74    76.6 1070.13    86.8 1062.07
   118.5  1042.4   125.5 1038.83   132.4 1036.31   142.7 1033.81   177.4 1030.11
   210.5  1030.7   217.1 1029.38  226.091025.852   236.9 1025.03  243.461025.851
   253.4 1027.81   263.2 1027.81   273.1 1028.99   293.2 1029.16   302.9 1030.74
   311.2 1035.03   322.1 1043.13   332.9 1052.86   349.9 1066.59   361.7 1070.91
   379.6 1080.43   415.2 1094.41   431.7 1099.27   458.7 1104.39   482.4 1111.36
#Mann= 3 ,-1,0
       0      .1       0  226.09    .045       0  243.46      .1       0
#XS Ineff= 2 , 0
                          266.06         1032.15
Permanent Ineff=
       F       F
Bank Sta=226.09,243.46
XS Rating Curve= 0 ,0
Exp/Cntr(USF)=0,0
Exp/Cntr=0.3,0.1

Type RM Length L Ch R = 1 ,9600    ,295.4,300.2,305.4
XS GIS Cut Line= 6
1663016.42908435543324.2102370111662966.21724251543395.857731506
1662922.88202734543457.0423204151662865.32604009543538.839400917
1662821.23754559543599.6811427621662760.54016042543666.426744178
#Sta/Elev= 30
       0 1103.25      47 1085.97    89.7 1067.08    95.1  1063.9   123.2 1040.35
   132.8 1034.09   143.3 1028.99   151.3 1026.58   158.7 1025.62   187.5 1022.62
   198.7  1022.2  204.37  1019.7   207.5 1018.62   211.5 1018.39  227.661019.698
   235.6 1020.56     249 1020.05   255.7 1021.19   259.7 1023.17   262.5 1025.13
   271.7 1032.82   276.4 1036.24     287 1042.28   310.7 1052.98   320.4 1056.32
   336.6 1062.98   358.7 1066.03     372 1067.32   407.5 1068.49   427.8 1071.51
#Mann= 3 ,-1,0
       0      .1       0  204.37    .045       0  227.66      .1       0
Bank Sta=204.37,227.66
XS Rating Curve= 0 ,0
Exp/Cntr(USF)=0,0
Exp/Cntr=0.3,0.1

Type RM Length L Ch R = 1 ,9300    ,306.3,301,291.2
XS GIS Cut Line= 6
1662880.41163984543204.2298339161662801.50989476543242.097540334
1662733.24559559543273.1617826671662642.22674875543314.580991179
1662573.96277767543345.6455615911662499.29494801543396.557533249
#Sta/Elev= 30
       0 1105.91      21 1101.26    37.2 1095.87    48.1 1093.82    52.9 1091.92
    66.3 1083.98    77.5 1078.61    84.9 1075.86    97.3 1072.81   124.5  1053.4
   138.6 1040.53   142.2 1038.84   149.3 1037.38   171.1 1022.71   192.7 1017.54
  204.631015.908   214.3 1015.12  222.521015.908   232.4 1018.76   261.2 1018.97
   267.7 1019.76   275.6 1022.12   300.4 1033.17   308.7 1037.96   326.1 1049.74
   342.3 1063.53     347 1066.68   377.7 1075.29   408.5 1089.32   427.9    1097
#Mann= 3 ,-1,0
       0      .1       0  204.63    .045       0  222.52      .1       0
Bank Sta=204.63,222.52
XS Rating Curve= 0 ,0
Exp/Cntr(USF)=0,0
Exp/Cntr=0.3,0.1

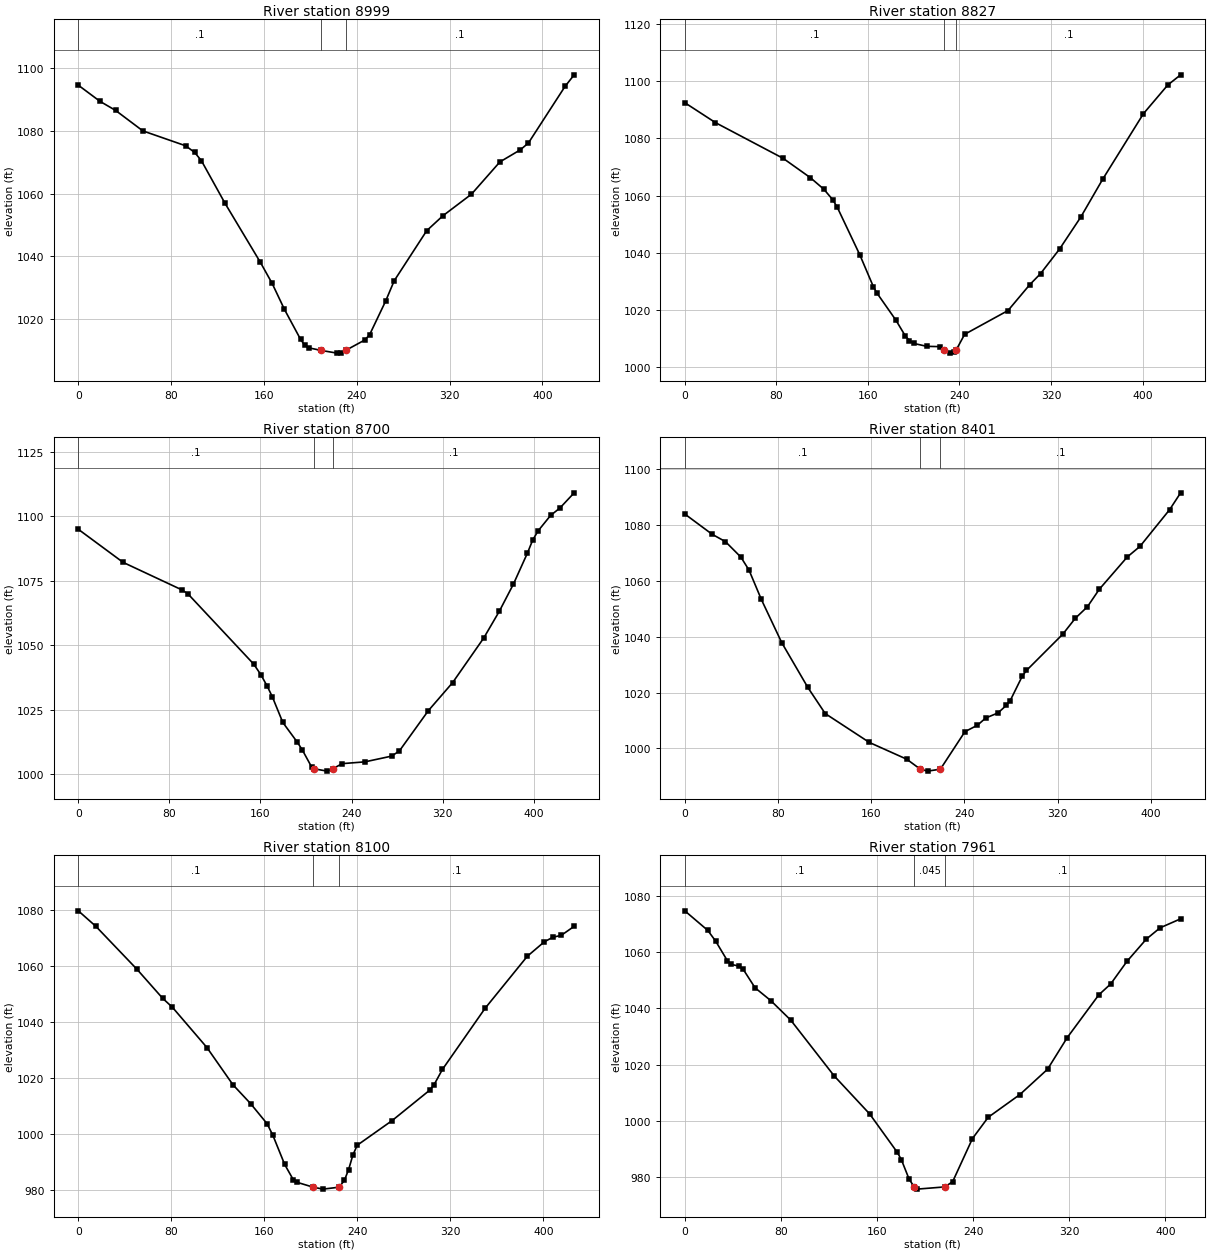
Type RM Length L Ch R = 1 ,8999    ,170.1,171.9,171.3
XS GIS Cut Line= 6
1662508.09283067542937.5279394981662489.74837917543024.337477177
1662470.86652717543098.0318835821662436.47289518543192.017588004
1662409.28889443543261.9177106771662378.30076742543343.750552252
#Sta/Elev= 30
       0 1094.58    18.7 1089.43    32.1 1086.55    55.6 1080.02    92.5 1075.27
   100.3 1073.14   106.1 1070.51   126.4 1056.96   156.9 1038.13   167.1 1031.37
   177.7 1023.09   191.6 1013.54   195.1 1011.71   198.5 1010.87  209.371010.032
     223 1009.17   226.5 1009.19  230.391010.032   246.8 1013.33     251 1014.98
   264.9 1025.76   272.3 1032.25   300.3  1048.2   314.2 1052.94   338.9 1059.85
   363.4 1070.13     381 1073.98     388 1076.17   419.5 1094.17   427.4 1097.89
#Mann= 3 ,-1,0
       0      .1       0  209.37    .045       0  230.39      .1       0
Bank Sta=209.37,230.39
XS Rating Curve= 0 ,0
Exp/Cntr(USF)=0,0
Exp/Cntr=0.3,0.1

Type RM Length L Ch R = 1 ,8827    ,126.2,127.3,126.3
XS GIS Cut Line= 2
1662425.39693563542900.7332911971662185.53770042543261.466471701
#Sta/Elev= 30
       0 1092.38    26.8 1085.42    85.9 1072.97   109.7 1066.22   121.5 1062.18
   129.2 1058.56   133.2  1055.9   152.9 1039.31   164.7 1028.24   167.6 1026.12
   184.4 1016.53   192.5 1011.12   196.2  1009.4   200.1 1008.39   211.4 1007.38
   223.2 1007.27  226.391006.005   231.7 1005.01   235.6 1005.27  236.961006.003
   244.5 1011.57   282.4 1019.87   301.3 1028.85   310.8 1032.74   327.4 1041.31
   345.9 1052.43   365.2 1065.74   400.7 1088.54     422 1098.56   433.2  1102.1
#Mann= 3 ,-1,0
       0      .1       0  226.39    .045       0  236.96      .1       0
Bank Sta=226.39,236.96
XS Rating Curve= 0 ,0
Exp/Cntr(USF)=0,0
Exp/Cntr=0.3,0.1

Type RM Length L Ch R = 1 ,8700    ,300.4,299.2,294.9
XS GIS Cut Line= 6
1662358.89234167542837.7135065941662301.13294275542903.440737337
1662251.62483968542959.7788792551662185.17254476543034.834175333
1662136.87211642543097.435100004 1662080.8686195 543172.49662967
#Sta/Elev= 30
       0 1094.95    39.3 1082.15    90.8 1071.52    96.1 1070.02   154.1  1042.7
   160.4 1038.59     166 1034.09   170.4 1030.07   179.6 1020.13   192.3 1012.51
   196.7 1009.51   204.9 1002.88  207.021002.183   218.6 1001.28  223.481002.181
   231.7 1004.18   251.7 1004.87   275.2  1007.1     282 1009.11   307.4 1024.69
   328.8 1035.59   356.1 1052.86   369.8 1063.23   382.1 1073.67   394.4 1085.69
   399.1 1090.79   403.8 1094.33   414.8 1100.32     423  1103.2   435.5 1109.08
#Mann= 3 ,-1,0
       0      .1       0  207.02    .045       0  223.48      .1       0
Bank Sta=207.02,223.48
XS Rating Curve= 0 ,0
Exp/Cntr(USF)=0,0
Exp/Cntr=0.3,0.1

Type RM Length L Ch R = 1 ,8401    ,299.2,300.6,301.1
XS GIS Cut Line= 6
1662033.36674601542687.8647249191662001.95506342542769.620795012
1661971.83209218542838.3056970091661932.71930951542930.346523419
1661906.97198567543000.928403258  1661881.473349543084.970229924
#Sta/Elev= 30
       0 1083.89    23.5 1076.63    34.9    1074    48.1 1068.48    55.1 1063.83
    65.7 1053.31    83.2 1037.85   105.6 1021.82   120.5 1012.49   158.4 1002.15
   190.5  996.15  202.14992.5767   208.3  991.89  219.32992.5778   240.4 1006.01
   251.1  1008.3   258.2 1010.89   268.8 1012.72   275.8 1015.38   279.3 1017.16
   289.7 1025.95   293.2  1027.9   324.4 1040.91   335.1 1046.57   345.5  1050.7
   355.7 1056.96   379.7 1068.51   390.6  1072.3   416.1 1085.47   425.5 1091.47
#Mann= 3 ,-1,0
       0      .1       0  202.14    .045       0  219.32      .1       0
Bank Sta=202.14,219.32
XS Rating Curve= 0 ,0
Exp/Cntr(USF)=0,0
Exp/Cntr=0.3,0.1

Type RM Length L Ch R = 1 ,8100    ,142.1,138.6,133
XS GIS Cut Line= 6
1661765.72784559542604.3130547551661726.76663743542683.769916832
1661690.87366459542750.1408470871661646.15196925542839.583253503
1661612.61069776542906.6654684251661574.66392326542985.519969508
#Sta/Elev= 30
       0 1079.58    15.2 1073.99    50.6 1058.62    72.6 1048.29    80.9 1045.13
   110.6 1030.74     133 1017.43   148.1 1010.73   162.4 1003.49   167.3  999.41
   177.5  988.95   184.9   983.5   188.5  982.53  202.05980.8352   210.5  980.14
  224.35 980.835   228.9  983.31   232.5  987.15   236.2  992.36   239.9  995.82
     270 1004.66   302.2 1015.48   305.9 1017.38   313.2 1022.92   349.8  1044.7
   386.2 1063.34   400.8  1068.5   408.1 1070.13   415.4 1070.82   426.5 1074.04
#Mann= 3 ,-1,0
       0      .1       0  202.05    .045       0  224.35      .1       0
Bank Sta=202.05,224.35
XS Rating Curve= 0 ,0
Exp/Cntr(USF)=0,0
Exp/Cntr=0.3,0.1

Type RM Length L Ch R = 1 ,7961    ,159.7,162.3,157.4
XS GIS Cut Line= 2
1661552.00902328542569.3715350721661521.79053695 542981.09841125
#Sta/Elev= 30
       0 1074.71    19.1 1067.77    25.7 1063.94    35.5 1056.94    38.8 1055.66
    45.4 1055.04    48.7 1053.87    58.5 1047.36    71.7 1042.76    88.2 1035.87
   124.3 1016.08   153.9 1002.53     177  988.83   180.3  986.28   186.8  979.31
  191.06 976.597   193.4  975.81  216.46976.5985     223  978.46   239.5  993.79
   252.6 1001.34     279 1009.43     302 1018.41   318.4 1029.66   344.7 1044.86
   354.6 1048.73   368.1 1056.74   384.2 1064.64   395.7 1068.67   412.8 1071.87
#Mann= 3 ,-1,0
       0      .1       0  191.06    .045       0  216.46      .1       0
Bank Sta=191.06,216.46
XS Rating Curve= 0 ,0
Exp/Cntr(USF)=0,0
Exp/Cntr=0.3,0.1

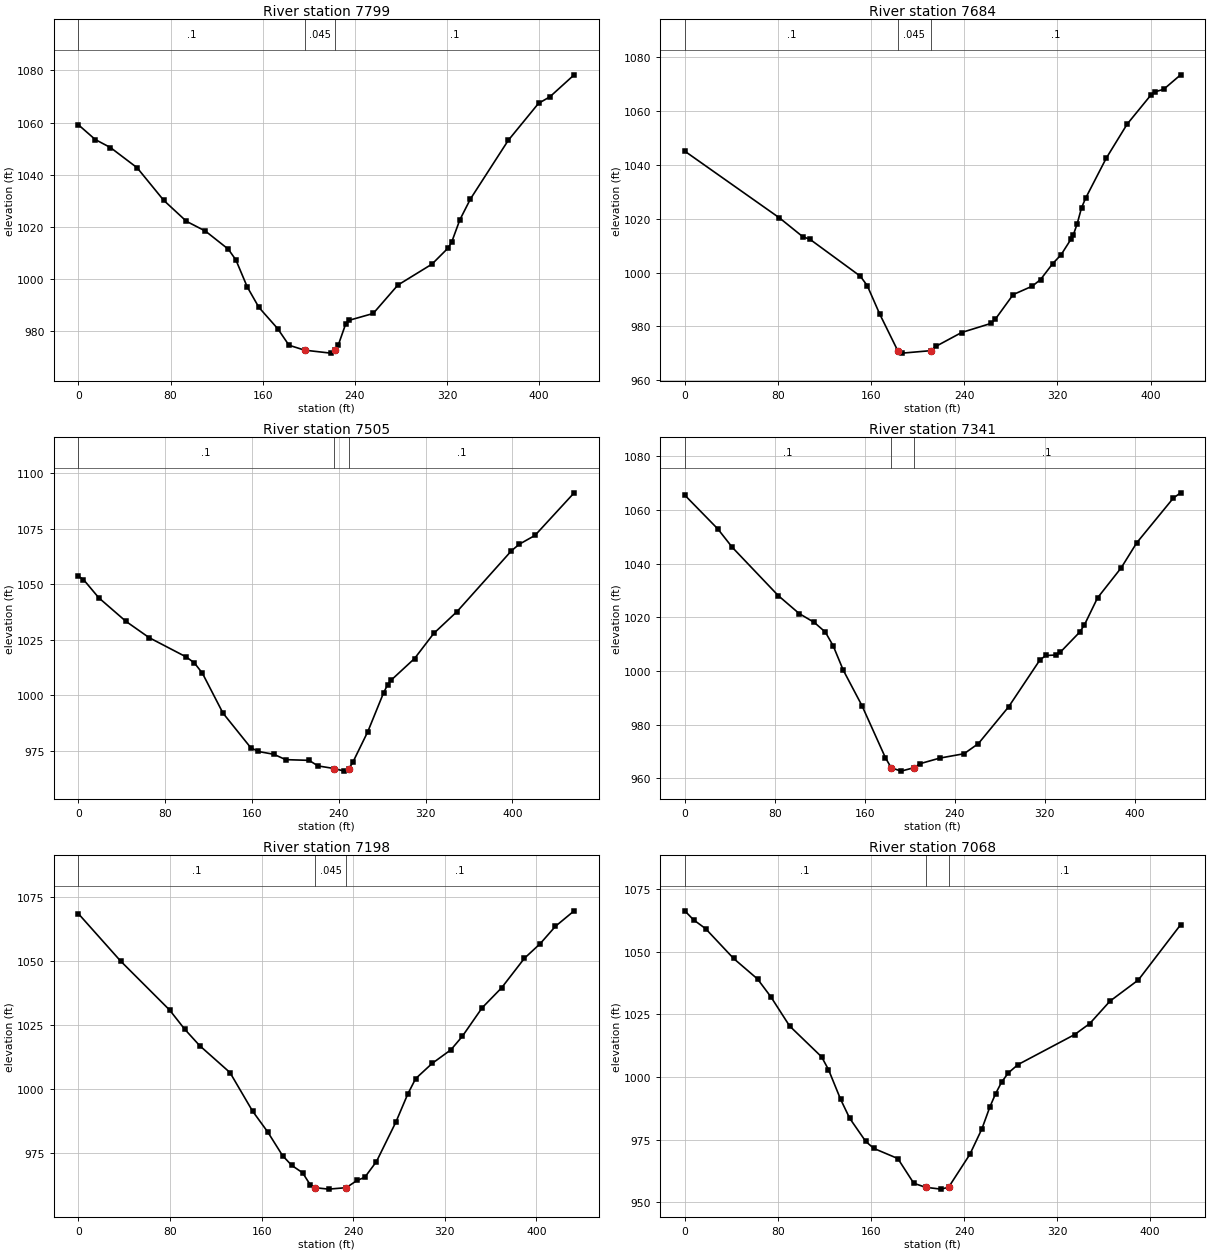
Type RM Length L Ch R = 1 ,7799    ,115.2,115.6,103.5
XS GIS Cut Line= 6
 1661364.3109975 542570.46666576  1661373.340507542661.045552835
1661381.26273526 542737.435491921661382.95826992 542837.43562001
1661382.95826992    542912.435471661382.95826992542999.935295001
#Sta/Elev= 30
       0 1059.17    14.7 1053.49    27.9 1050.41      51 1042.67    74.1 1030.16
    93.8 1022.11   110.3 1018.35   130.1 1011.43   136.7 1007.32   146.6  996.91
   156.7  989.07     173  980.91   182.8  974.55  196.31972.6522   218.9  971.51
  223.03972.6512   225.5  974.47     232  982.69   235.3  984.15   255.9  986.73
   277.3  997.63   306.9 1005.67   320.6 1011.72   323.9 1013.99   331.1 1022.69
   340.3 1030.69   373.1 1053.18   399.4 1067.39   409.2 1069.88   430.3 1078.33
#Mann= 3 ,-1,0
       0      .1       0  196.31    .045       0  223.03      .1       0
Bank Sta=196.31,223.03
XS Rating Curve= 0 ,0
Exp/Cntr(USF)=0,0
Exp/Cntr=0.3,0.1

Type RM Length L Ch R = 1 ,7684    ,172.2,178.5,188.5
XS GIS Cut Line= 4
1661234.46561435542593.0666056621661253.26236274542742.919890482
 1661302.6114173542847.680394546 1661360.5310956542995.674959159
#Sta/Elev= 30
       0 1045.16    81.3 1020.36   101.1 1013.44   107.7 1012.34   150.7  998.71
   156.7  995.18   167.4  984.61  182.86971.0139   186.9   970.1  211.17 971.016
   215.9  972.68   237.7  977.76   263.1  981.17   266.7  982.73     282  991.86
   298.4  994.99   305.5  997.45     316  1003.4   323.1 1006.63   331.8 1012.56
   333.7  1014.1   336.9 1018.08   340.7 1024.11   344.2 1027.68   361.8 1042.46
   379.9 1055.23   400.6  1066.2   404.1 1067.27   411.2 1068.14   425.8 1073.54
#Mann= 3 ,-1,0
       0      .1       0  182.86    .045       0  211.17      .1       0
Bank Sta=182.86,211.17
XS Rating Curve= 0 ,0
Exp/Cntr(USF)=0,0
Exp/Cntr=0.3,0.1

Type RM Length L Ch R = 1 ,7505    ,161.3,163.8,163.4
XS GIS Cut Line= 6
 1661201.2978721542570.972242177 1661160.6975596542667.053414837
1661123.12742476542748.6841570881661081.54023759542839.702675834
1661052.40774992542908.9216975121661016.19719243542988.806380257
#Sta/Elev= 30
       0 1053.67     4.7 1052.17    18.9 1043.91    43.8 1033.36    65.2 1026.01
    99.5 1017.28     107  1014.6   114.4 1009.93   133.3  992.02   158.9  976.45
   165.8  974.74   180.2  973.47   191.1  971.06   212.7  970.74   220.8  968.25
  235.67967.0627   245.2  965.89  249.45967.0598     253  969.87   266.8  983.66
   281.3  1001.1   285.1  1004.8   288.5 1006.94   309.9  1016.6   327.6 1027.91
   349.1 1037.76   399.2 1065.11   406.4 1068.05   420.9 1072.03     457  1091.2
#Mann= 3 ,-1,0
       0      .1       0  235.67    .045       0  249.45      .1       0
Bank Sta=235.67,249.45
XS Rating Curve= 0 ,0
Exp/Cntr(USF)=0,0
Exp/Cntr=0.3,0.1

Type RM Length L Ch R = 1 ,7341    ,145,143,138.2
XS GIS Cut Line= 2
1661133.72690234542516.7274779481660849.48426534542853.852466013
#Sta/Elev= 30
       0 1065.57    29.4 1052.96    42.2 1046.13    83.1 1028.12   101.7 1021.43
   115.2  1018.1     125 1014.51     132 1009.37   140.9 1000.34   157.6  987.06
   178.5   967.6   183.6963.9043   192.4  962.66  203.55963.9046   209.6  965.48
   226.8  967.52   248.4  969.15   261.1  972.92     288  986.63   315.9 1004.15
   321.2 1005.78   329.8 1005.95   334.1 1007.06   351.2 1014.48   355.5 1017.25
   367.1 1027.27   388.1 1038.45     402 1047.83   434.6 1064.52     441 1066.44
#Mann= 3 ,-1,0
       0      .1       0   183.6    .045       0  203.55      .1       0
Bank Sta=183.6,203.55
XS Rating Curve= 0 ,0
Exp/Cntr(USF)=0,0
Exp/Cntr=0.3,0.1

Type RM Length L Ch R = 1 ,7198    ,126.1,129.8,126.6
XS GIS Cut Line= 6
1660907.35981168542430.2002139991660900.66592743542520.300427511
1660893.51338267 542598.125731171660867.31461617542696.527437255
1660845.55448909542768.2605615111660825.80190392542853.619970843
#Sta/Elev= 30
       0 1068.49    36.9 1049.97    79.7 1030.85    92.8 1023.39     106 1016.91
   132.4 1006.43   152.1  991.39   165.3  983.27   178.3     974   186.3  970.19
   195.8   967.3   202.6  962.52  206.48961.4777   218.5  960.91  233.94961.4774
   243.3   964.3   250.1  965.52   260.3  971.68   277.3  987.14   287.6  998.02
   294.5 1004.05   308.9    1010   325.3 1015.32   335.2 1020.54   352.6 1031.74
   369.5 1039.49   389.5 1051.06   403.2 1056.73   416.6 1063.55   432.9 1069.58
#Mann= 3 ,-1,0
       0      .1       0  206.48    .045       0  233.94      .1       0
Bank Sta=206.48,233.94
XS Rating Curve= 0 ,0
Exp/Cntr(USF)=0,0
Exp/Cntr=0.3,0.1

Type RM Length L Ch R = 1 ,7068    ,172.7,169,162.8
XS GIS Cut Line= 2
1660832.80224958542404.1210815741660703.53323105542810.285867614
#Sta/Elev= 30
       0 1066.34     7.5 1062.75    17.8 1059.25    41.9 1047.33    62.5 1039.12
    73.9 1032.05    90.1 1020.34   117.6 1008.02   123.5 1002.94   133.9  991.09
   141.7  983.51   155.5  974.26   162.4  971.47   183.1  967.41   196.8  957.54
  206.94 955.928   220.1  955.19  226.73 955.928     245  969.05   255.4  979.27
   262.2  987.98   267.1  993.25   272.3  997.91     278 1001.56   286.3  1004.9
     335 1016.89   348.1 1021.32   365.5 1030.28   389.9 1038.74   426.2 1060.79
#Mann= 3 ,-1,0
       0      .1       0  206.94    .045       0  226.73      .1       0
Bank Sta=206.94,226.73
XS Rating Curve= 0 ,0
Exp/Cntr(USF)=0,0
Exp/Cntr=0.3,0.1

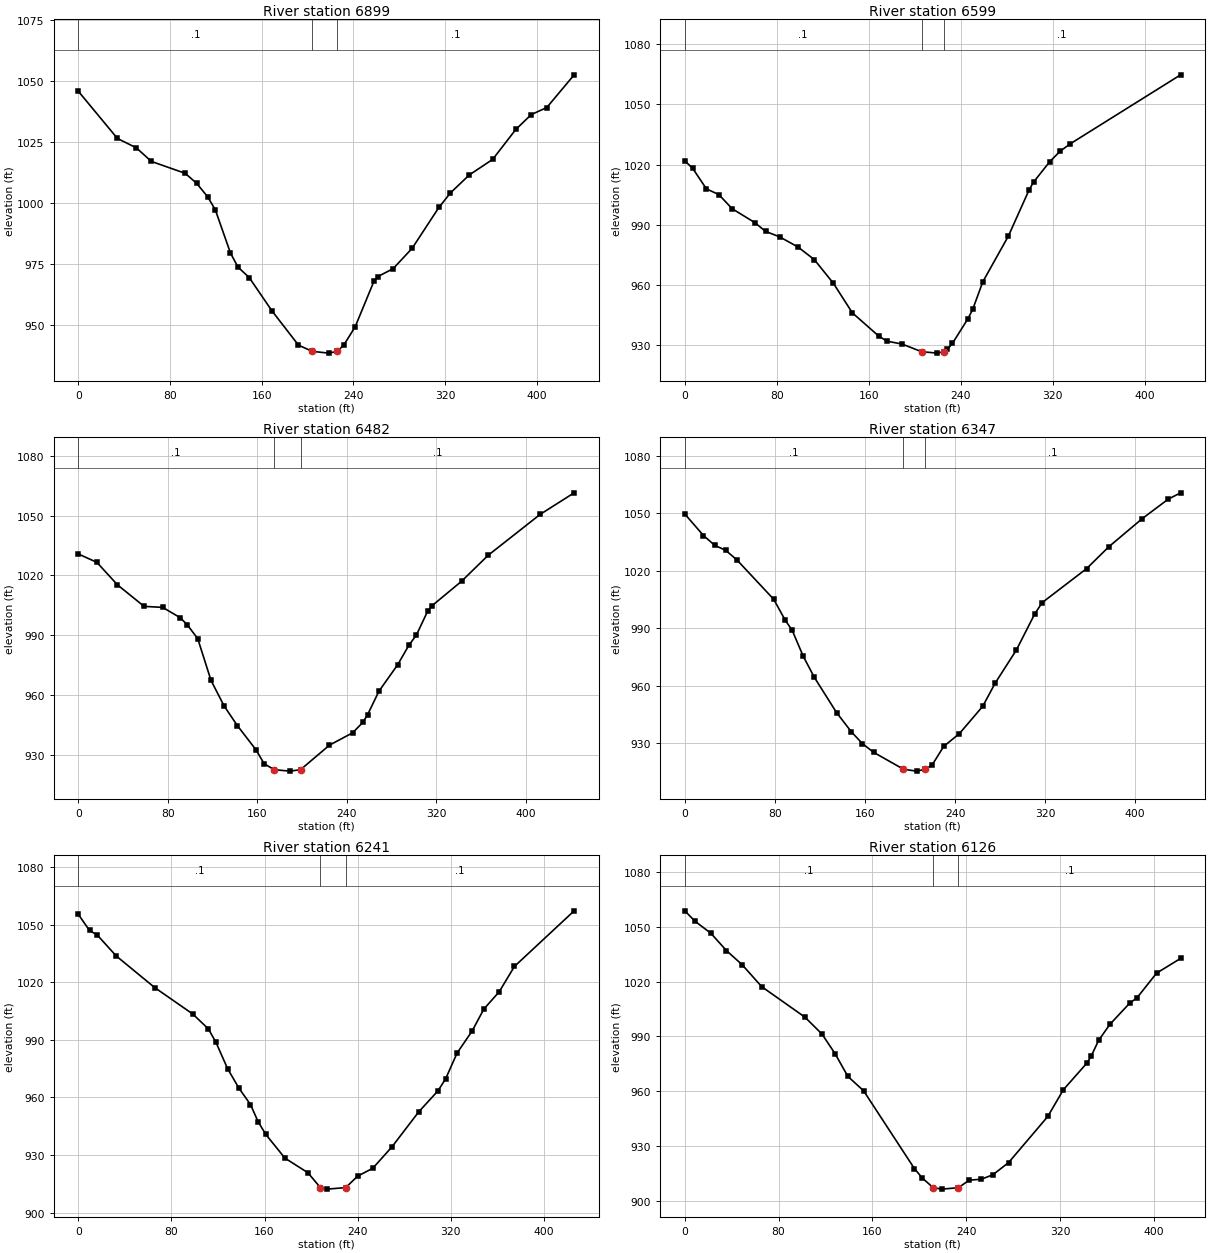
Type RM Length L Ch R = 1 ,6899    ,291.1,300.8,308.4
XS GIS Cut Line= 6
1660615.23539592542341.0166653391660612.58940384542429.889191002
 1660617.0175446542505.6383833441660628.67762625542604.962331668
1660615.96899025542681.0917725861660594.88996418542769.138512507
#Sta/Elev= 30
       0 1045.85    34.1  1026.5    50.6 1022.66    63.7 1017.09    93.2 1012.21
   103.1 1008.16   112.9 1002.54   119.5  997.23   132.7  979.54   139.2   973.8
   149.1  969.44   168.8  955.88     192  941.78  203.99 939.224   218.4  938.49
  225.88939.2257   231.6  941.83   241.5   949.3     258  968.13   261.3   969.9
   274.6  973.11   291.2  981.48   314.5  998.21   324.5 1004.14   341.1 1011.57
   361.4 1017.91   381.6  1030.2   395.1  1036.3   408.6 1039.17   432.5 1052.59
#Mann= 3 ,-1,0
       0      .1       0  203.99    .045       0  225.88      .1       0
Bank Sta=203.99,225.88
XS Rating Curve= 0 ,0
Exp/Cntr(USF)=0,0
Exp/Cntr=0.3,0.1

Type RM Length L Ch R = 1 ,6599    ,118.1,116.1,114.4
XS GIS Cut Line= 6
1660471.83837301542307.1328748321660420.86504975542381.624195665
1660372.40320443 542440.296322421660306.02079126542515.168876082
1660254.72529018542569.8846459241660216.19452734542650.893014088
#Sta/Elev= 30
       0  1021.9     6.9 1018.11    18.8 1007.91    29.6 1005.07    41.2  998.01
    60.9   991.1    70.2  986.73    82.4  984.02    98.3  978.99   112.6  972.67
   129.2  960.86   145.7  946.12   168.5  934.62   175.7  932.03   188.9  930.58
  205.86926.7834   219.6  926.06  225.17926.7838   228.4     928   232.7  930.92
   245.9  942.95   250.3  947.82   259.1  961.61   281.3  984.34   299.3 1007.34
   303.2 1011.27   317.3 1021.47   326.3 1026.67   335.3 1030.43   431.1 1064.75
#Mann= 3 ,-1,0
       0      .1       0  205.86    .045       0  225.17      .1       0
Bank Sta=205.86,225.17
XS Rating Curve= 0 ,0
Exp/Cntr(USF)=0,0
Exp/Cntr=0.3,0.1

Type RM Length L Ch R = 1 ,6482    ,142.2,135,126.2
XS GIS Cut Line= 3
1660359.44995916542239.9053680011660234.11500982542430.974968379
1660189.36804186542640.941510315
#Sta/Elev= 30
       0 1030.73    16.6 1026.52    34.9 1015.28    58.8 1004.43    75.4 1003.93
    91.1  998.74    97.3  995.23   106.7  988.28   118.6  967.27   130.3  954.47
   142.1  944.63   158.9  932.38     166  925.54  175.03922.4611   189.2  921.75
  198.59922.4608   224.5  934.79   245.2  940.99   254.2  946.16   258.6  950.11
   268.7  961.86   285.5  975.18   295.5  984.95   302.2  990.07   312.3 1002.09
   315.9 1004.64   342.5 1017.01   366.4  1030.1   412.9 1050.64   443.2 1061.42
#Mann= 3 ,-1,0
       0      .1       0  175.03    .045       0  198.59      .1       0
Bank Sta=175.03,198.59
XS Rating Curve= 0 ,0
Exp/Cntr(USF)=0,0
Exp/Cntr=0.3,0.1

Type RM Length L Ch R = 1 ,6347    ,104.3,106.5,106.9
XS GIS Cut Line= 4
1660139.53870224542204.343875562 1660135.2892276542369.223491574
1660167.58523486542465.2616184261660183.73323849542638.640183716
#Sta/Elev= 30
       0 1049.64    16.6 1038.38    26.5 1033.29    36.3 1030.64    46.1 1025.75
      79 1005.04    89.1  994.22    95.4  988.83   105.2  975.27   115.1  964.22
   134.8  945.85   147.9  935.82   157.7  929.66   167.7  925.08  194.25916.2375
   205.8  915.25   213.7916.2357   219.6  918.38     230   928.2   243.9  934.85
   264.6  949.12   275.8  961.37   294.4  978.43   310.8  997.39   317.4 1003.31
     357 1021.14   376.7 1032.56   406.4 1047.25   429.3 1057.36   440.4  1060.7
#Mann= 3 ,-1,0
       0      .1       0  194.25    .045       0   213.7      .1       0
Bank Sta=194.25,213.7
XS Rating Curve= 0 ,0
Exp/Cntr(USF)=0,0
Exp/Cntr=0.3,0.1

Type RM Length L Ch R = 1 ,6241    ,111.6,114.7,116.2
XS GIS Cut Line= 4
1660045.99539268542204.8305860011660060.49847395542369.223491574
1660058.79868409542466.1115133541660071.88584752 542629.66018619
#Sta/Elev= 30
       0 1055.33     9.6 1046.93    16.2  1044.6    32.6 1033.64    65.6 1017.21
    98.3 1003.45   111.7  995.71   118.3  988.64   128.2  975.03     138  964.82
   147.9  956.33   154.5  947.33   161.1  940.74   177.5  928.42   197.2  920.84
  207.99 913.067   213.6  912.28  229.74913.0664   239.9  919.02     253  923.15
   269.4  934.25   292.5  952.54   308.9  963.39   315.5  969.61   325.4  983.11
   338.4  994.66   348.4 1006.01   361.6 1015.02   374.7 1028.22     426 1057.16
#Mann= 3 ,-1,0
       0      .1       0  207.99    .045       0  229.74      .1       0
Bank Sta=207.99,229.74
XS Rating Curve= 0 ,0
Exp/Cntr(USF)=0,0
Exp/Cntr=0.3,0.1

Type RM Length L Ch R = 1 ,6126    ,124,126.3,127.5
XS GIS Cut Line= 2
  1659989.778717542195.9025302731659909.23417468542611.016709904
#Sta/Elev= 30
       0 1058.71     8.8 1052.96    22.2 1046.45    35.5 1036.95    48.9  1029.2
    65.6 1017.18   102.4 1000.51     117  991.25   128.2  980.45   139.1  968.03
   152.5  960.17   195.9  917.51   202.6  912.37  211.84907.1036   219.3  906.31
  233.39907.1047   242.7  911.25   252.8  911.69   262.8  914.19   276.2  920.87
   309.6  946.09   322.9  960.75     343  975.36   346.5  978.97     353  987.82
   362.7  996.63   379.3 1008.03   385.7 1011.09   402.4 1024.59   422.9 1032.66
#Mann= 3 ,-1,0
       0      .1       0  211.84    .045       0  233.39      .1       0
Bank Sta=211.84,233.39
XS Rating Curve= 0 ,0
Exp/Cntr(USF)=0,0
Exp/Cntr=0.3,0.1

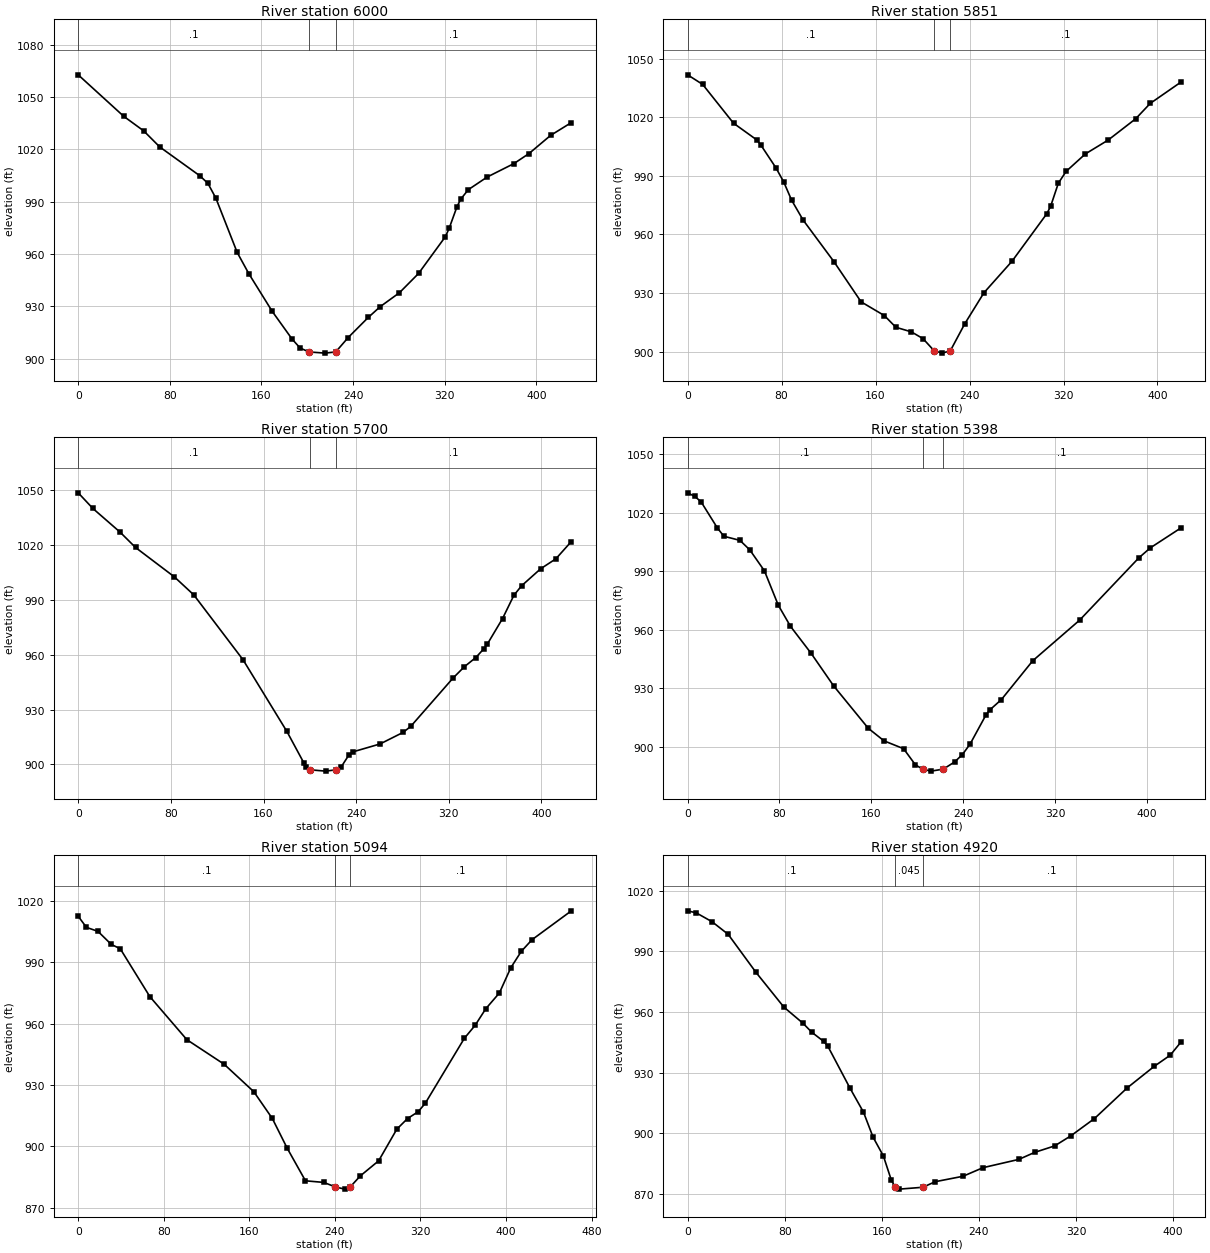
Type RM Length L Ch R = 1 ,6000    ,152.3,149.5,143.8
XS GIS Cut Line= 6
1659904.12592576542170.5822949261659873.65945126 542252.60706526
1659847.54565834542322.9140112551659812.72781458542416.656934008
1659798.07856567542491.4084249291659785.82891826542582.409883335
#Sta/Elev= 30
       0 1062.79    39.7 1039.02    57.2 1030.63    71.2 1021.42   106.2 1004.87
   113.2 1000.56   120.2  992.02   138.8  960.88     149  948.65   169.4  927.08
   186.7  911.22   193.7  906.09  201.39903.8461   215.4  903.15  224.82903.8453
   235.7  912.11   253.2  923.62   263.7  929.84   280.4  937.78   297.1  948.83
   320.5  969.92   323.8  974.69   330.5  986.86   333.8  991.34   340.5  996.89
     357 1004.16   380.3 1011.85   393.5 1017.62   412.4 1028.05   430.5  1035.4
#Mann= 3 ,-1,0
       0      .1       0  201.39    .045       0  224.82      .1       0
Bank Sta=201.39,224.82
XS Rating Curve= 0 ,0
Exp/Cntr(USF)=0,0
Exp/Cntr=0.3,0.1

Type RM Length L Ch R = 1 ,5851    ,149.2,150.5,151.4
XS GIS Cut Line= 2
1659707.37768159542165.5828558931659672.95693701542583.986128894
#Sta/Elev= 30
       0 1041.66    12.8 1036.77    39.1  1016.9    58.8  1008.4    62.1 1005.97
    75.3  993.98    81.9  986.75    88.5  977.57    98.3  967.38   124.6  946.04
   147.7  925.51   167.5  918.48   177.3  912.49   190.5  910.15   200.4  906.68
  209.83900.4929   216.8  899.27  223.68900.4905     236  914.35   252.3  930.19
   276.1  946.24   305.7  970.53     309  974.35   315.6  986.22   322.2  992.25
   338.6 1001.19     358 1008.28   381.4 1019.16   393.8 1027.03   419.8 1037.88
#Mann= 3 ,-1,0
       0      .1       0  209.83    .045       0  223.68      .1       0
Bank Sta=209.83,223.68
XS Rating Curve= 0 ,0
Exp/Cntr(USF)=0,0
Exp/Cntr=0.3,0.1

Type RM Length L Ch R = 1 ,5700    ,305.3,302,296.2
XS GIS Cut Line= 6
 1659583.9487446542152.7404670861659566.25028917542238.431896761
1659551.05445342542311.8763036731659530.79268293542409.801960841
 1659521.0036605542484.333307832 1659514.0312335   542572.152686
#Sta/Elev= 30
       0 1048.58    12.7 1040.01    36.1  1027.1    49.5 1018.67      83  1002.6
    99.8  992.73   142.3  957.24   180.2  917.98     195  900.58     197  898.62
  200.29 896.985   213.7  896.28  222.43 896.985   227.1  898.61   233.8  905.17
   237.2  906.83   260.6  911.14   280.5  917.47   287.1  920.75   323.5  947.11
   333.4   953.4   343.3  958.44     350  963.06   353.2  965.74   366.4  979.79
   376.2  992.52   382.8  997.69   399.3 1007.02   412.4 1012.45   425.8 1021.94
#Mann= 3 ,-1,0
       0      .1       0  200.29    .045       0  222.43      .1       0
Bank Sta=200.29,222.43
XS Rating Curve= 0 ,0
Exp/Cntr(USF)=0,0
Exp/Cntr=0.3,0.1

Type RM Length L Ch R = 1 ,5398    ,303.8,304,301.7
XS GIS Cut Line= 6
1659171.65626208 542154.257852511659204.82122201542236.187478676
1659233.92122942 542305.906827421659261.03403609542402.246857837
1659280.92441626542474.607605502 1659307.9883385542560.929939419
#Sta/Elev= 30
       0 1030.28     6.4 1028.41    11.8 1025.61    25.9 1012.28    31.6 1007.99
    45.6 1005.88    54.2 1000.98    66.9  990.26      79   972.6    89.6  961.78
   107.4  948.06   127.2   931.2   157.4  909.43   171.1     903   188.1  898.98
   198.4   890.7  204.73888.4816     212  887.47  222.63888.4826   232.5  892.16
   239.3  895.94   246.1  901.43   259.7  916.14   263.1  918.82   273.3   924.2
   300.6  944.11   341.4  964.93     393  996.91     403 1002.04   429.5 1012.21
#Mann= 3 ,-1,0
       0      .1       0  204.73    .045       0  222.63      .1       0
Bank Sta=204.73,222.63
XS Rating Curve= 0 ,0
Exp/Cntr(USF)=0,0
Exp/Cntr=0.3,0.1

Type RM Length L Ch R = 1 ,5094    ,171.6,174,172.7
XS GIS Cut Line= 6
1658947.21117292542305.0734957611658980.41484667542403.761618584
1659010.91052058542491.0285044161659039.36125109542589.064725667
1659051.57218467 542663.024879591659065.81756301542749.310796261
#Sta/Elev= 30
       0 1012.46     7.7 1007.03    18.5 1005.07      31  998.66    39.3  996.59
      67  973.15   101.6  952.09   136.4   940.1   164.2  926.64   181.5  913.55
   195.4  899.01   212.5  883.06   229.6  882.28  240.54880.0502   249.2  878.99
  254.32880.0508   263.8  885.47   280.9  892.83   297.9  908.31   307.9  913.51
   317.9  916.86   324.6  921.06   361.1   952.8   371.1  959.09   381.1  967.23
   393.8  974.93   404.4   987.2   414.3   995.3   424.3 1000.98   461.1 1015.12
#Mann= 3 ,-1,0
       0      .1       0  240.54    .045       0  254.32      .1       0
Bank Sta=240.54,254.32
XS Rating Curve= 0 ,0
Exp/Cntr(USF)=0,0
Exp/Cntr=0.3,0.1

Type RM Length L Ch R = 1 ,4920    ,195.7,202.5,198.1
XS GIS Cut Line= 2
1658856.84328127542325.3755235881658861.94265083542731.625299121
#Sta/Elev= 30
       0 1010.14     7.1 1009.14    20.2 1004.72    33.4  998.51    56.3  979.68
    79.3  962.45    95.1  954.42   102.3  949.99   112.1  945.46   115.4  943.22
   133.9  922.17   144.9  910.41   152.8  898.02   161.3  888.69   167.9  876.62
  171.12873.1853   174.4  872.27  193.81873.1865     204  875.95   226.9  878.64
   243.4   882.9   272.9     887     286  890.49   302.4  893.68   315.7  898.65
   335.2  907.23   362.2  922.44   384.4  933.08   397.6  938.61   406.3     945
#Mann= 3 ,-1,0
       0      .1       0  171.12    .045       0  193.81      .1       0
Bank Sta=171.12,193.81
XS Rating Curve= 0 ,0
Exp/Cntr(USF)=0,0
Exp/Cntr=0.3,0.1