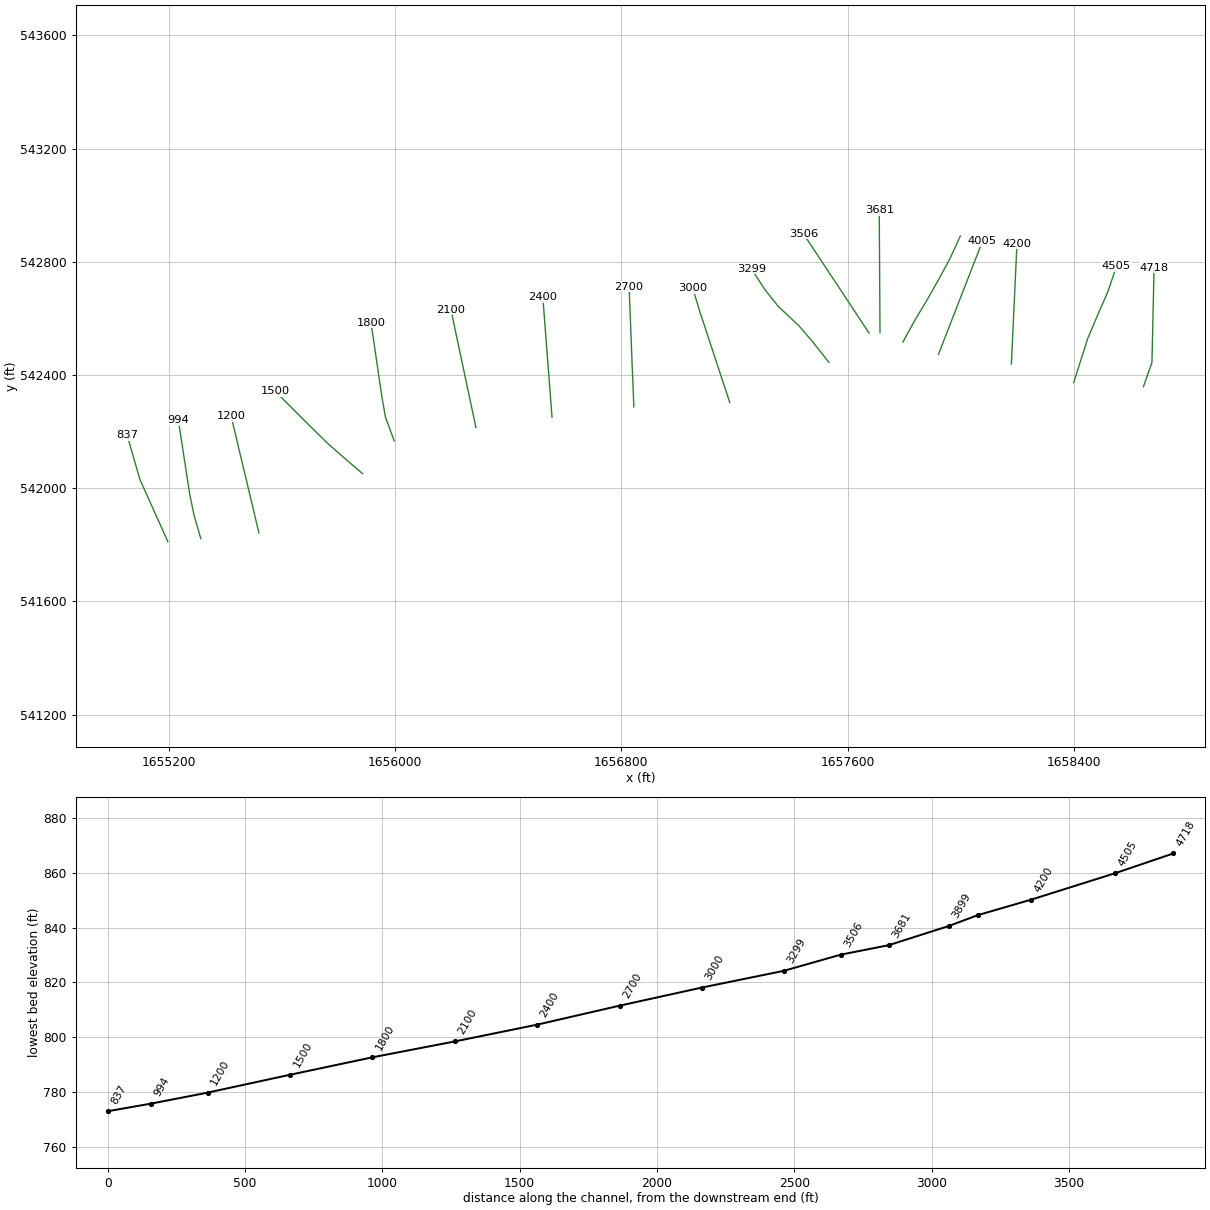
HEC-RAS study BruceRn.prj: BruceRn

--- BruceRn.g01 (geometry) --- (continued)

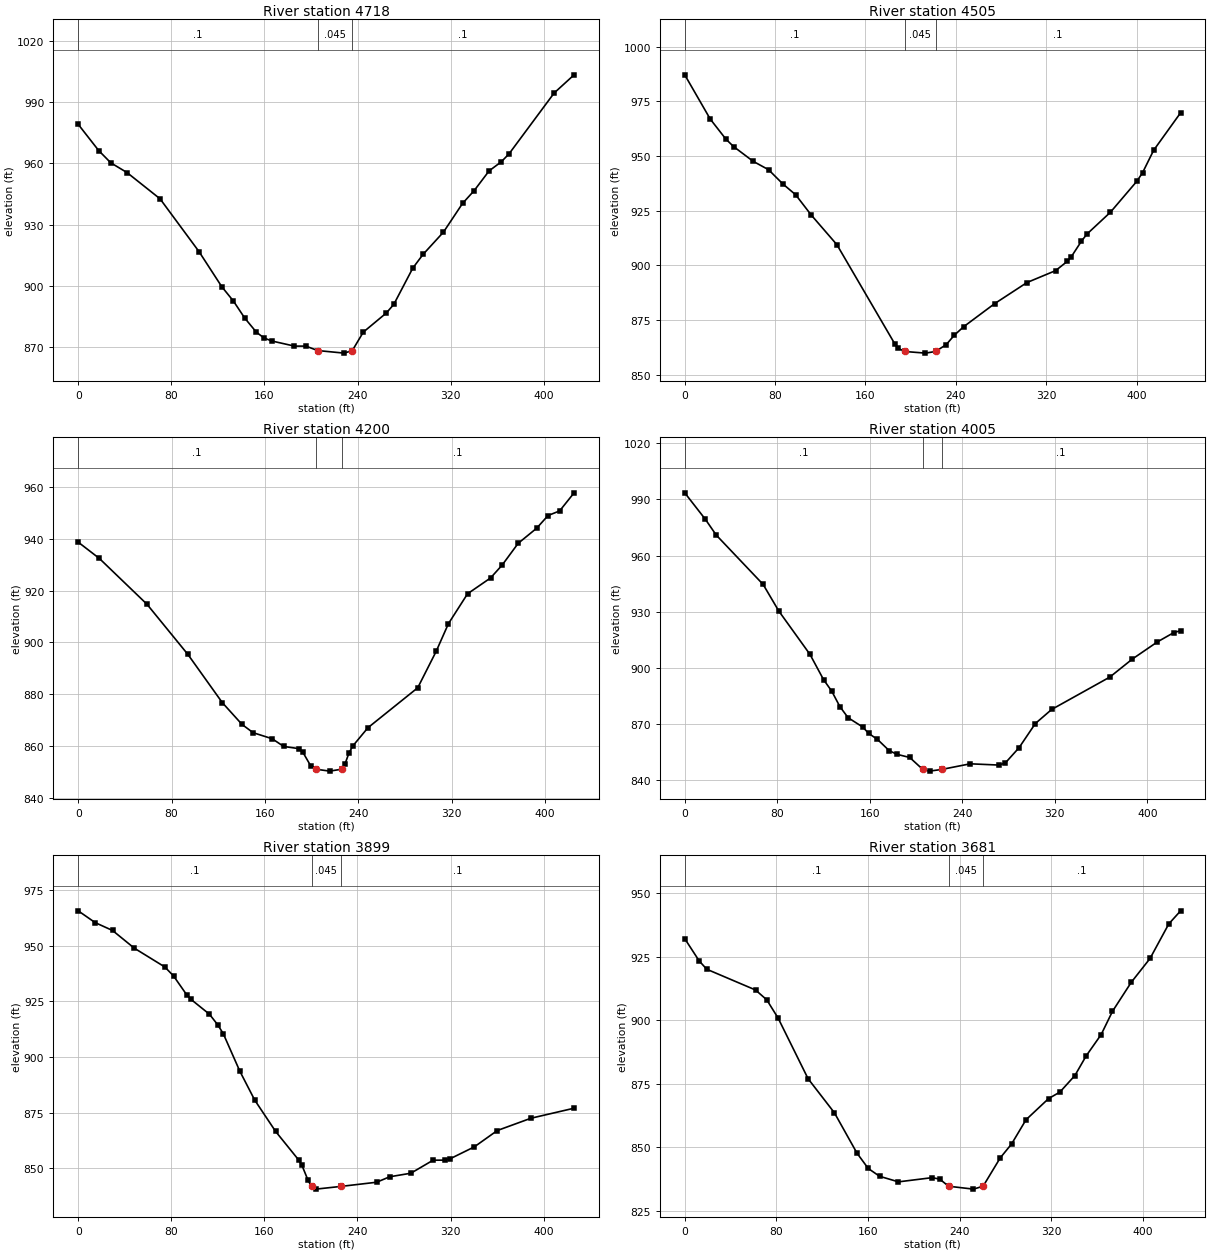
Type RM Length L Ch R = 1 ,4718    ,219.1,212.9,209.2
XS GIS Cut Line= 3
1658644.30561076542358.5674832611658674.52733509542444.455762923
1658681.99072912542779.371512406
#Sta/Elev= 30
       0  979.08    17.6  966.24      28  960.23    41.9  955.48    70.3  942.62
   103.8  916.75   123.4  899.53   133.3  892.58   143.1  884.19     153  877.35
   159.5  874.52   166.1  873.03   185.8  870.49   195.6   870.5  205.71868.3214
   228.5  867.06  235.49868.3188   244.9  877.34   264.6  886.66   271.1  890.91
   287.5  908.75   296.2  915.37   313.8  926.32   330.2  940.38   340.2  946.66
     353   956.3   363.4  960.71   370.1  964.62   408.9  994.44     426 1003.32
#Mann= 3 ,-1,0
       0      .1       0  205.71    .045       0  235.49      .1       0
Bank Sta=205.71,235.49
XS Rating Curve= 0 ,0
Exp/Cntr(USF)=0,0
Exp/Cntr=0.3,0.1

Type RM Length L Ch R = 1 ,4505    ,299,304.6,307.7
XS GIS Cut Line= 6
1658398.00951542542373.3069550841658424.54030226542456.688021928
1658447.28107043542528.1570390911658486.46734376542620.914399505
1658519.02633376542695.0435163381658549.34353034542784.898651585
#Sta/Elev= 30
       0   987.2    22.6  966.93    36.4  957.79    43.2  954.38    60.5  947.64
    74.2  943.77    86.8  937.29    98.2   932.3   112.1  922.96   134.7  909.46
   185.9  864.11   188.7  862.11  194.72860.5744   213.1  859.82  222.04860.5742
   231.5  863.72   238.6  867.99   246.8  871.86   274.3  882.45   302.9  892.11
   328.3  897.58   338.8  901.88   342.3  903.99   351.2  911.07   356.1  914.32
   376.9  924.33   400.2  938.46   405.3  942.39   415.1  952.65     439  969.84
#Mann= 3 ,-1,0
       0      .1       0  194.72    .045       0  222.04      .1       0
Bank Sta=194.72,222.04
XS Rating Curve= 0 ,0
Exp/Cntr(USF)=0,0
Exp/Cntr=0.3,0.1

Type RM Length L Ch R = 1 ,4200    ,197,195,191.6
XS GIS Cut Line= 6
 1658177.7783286542438.7431759241658181.89807101542526.146216333
1658185.38231601542601.0650297551658190.02928834542700.957218423
1658193.51418951542775.8760318461658197.57979818542863.281696916
#Sta/Elev= 30
       0  938.68    18.1   932.4    58.9  914.71      94  895.31   123.5  876.68
   140.4  868.26   149.9  865.07   166.2  862.74   176.1  859.76   189.2   858.9
   192.5  857.55   199.1  852.38  203.96  850.95   215.5  850.22  225.66850.9485
   228.6   852.9   231.9  857.04   235.2  859.86   248.3  866.98     291  882.43
   306.8   896.5   317.3  907.19   333.7  918.74   353.4  924.85   363.3   929.8
   377.1  938.24   392.9  944.06   402.7  948.98   412.6  950.75     425  957.74
#Mann= 3 ,-1,0
       0      .1       0  203.96    .045       0  225.66      .1       0
Bank Sta=203.96,225.66
XS Rating Curve= 0 ,0
Exp/Cntr(USF)=0,0
Exp/Cntr=0.3,0.1

Type RM Length L Ch R = 1 ,4005    ,108,106.1,103.4
XS GIS Cut Line= 2
1657920.25907073542473.2572410421658075.78984253542872.707857152
#Sta/Elev= 30
       0  993.57    17.9  979.33    27.2  970.97    67.8  944.49    81.3  930.29
   108.3  907.03     120  893.55   127.1  887.35   134.1  879.12   141.2  873.17
   153.9  868.15     159  864.75   166.6  861.55   176.7  855.55   183.4  853.56
   194.5  851.86  205.84845.4377   211.6  844.55  221.98 845.436   246.8  848.47
   271.4   847.8   277.1  848.89     289  857.08   303.1  870.03   317.2  877.57
   367.5  894.91     387  904.58   408.7  913.78   422.8  918.73   428.7  919.75
#Mann= 3 ,-1,0
       0      .1       0  205.84    .045       0  221.98      .1       0
Bank Sta=205.84,221.98
XS Rating Curve= 0 ,0
Exp/Cntr(USF)=0,0
Exp/Cntr=0.3,0.1

Type RM Length L Ch R = 1 ,3899    ,205.7,217.7,221.7
XS GIS Cut Line= 6
1657794.83290026542516.5540439191657837.12710701 542593.93741934
1657875.98267233542658.4553349171657925.37102501 542745.43711634
1657960.92836858542811.4727454191657997.53557885542891.139580846
#Sta/Elev= 30
       0  965.66    14.6  960.35    29.5  956.83    48.2  948.88    74.4  940.44
    81.9  936.42    93.2  927.95      97  925.83   112.8  919.19   119.9  914.44
   124.7  910.43   138.9   893.6   151.7   880.6   169.7  866.49   189.5  853.67
   192.3  851.26   197.6  844.48  200.51841.7831   204.3  840.58   225.5841.7829
   256.5  843.68   267.7  846.13   285.9  847.73     305  853.58   314.9  853.61
   319.8  854.26   340.5  859.59   360.2  866.92   389.1  872.44   426.2  876.95
#Mann= 3 ,-1,0
       0      .1       0  200.51    .045       0   225.5      .1       0
Bank Sta=200.51,225.5
XS Rating Curve= 0 ,0
Exp/Cntr(USF)=0,0
Exp/Cntr=0.3,0.1

Type RM Length L Ch R = 1 ,3681    ,162.8,175.5,181.1
XS GIS Cut Line= 2
1657713.68253132 542549.555323241657711.03075557542982.518979694
#Sta/Elev= 30
       0  932.13    12.6  923.38    19.2   920.1    61.8  911.94    71.6  908.08
    81.5  900.91   107.7  877.04   130.7  863.63   150.4  847.77   160.2  841.75
   170.1  838.67   186.6  836.47     216  838.12   222.6  837.56  230.42 834.744
   252.1  833.61  260.53834.7443   275.5  845.91   285.4  851.37     298   860.9
   317.7  869.22   327.6  871.79   340.7   878.3   350.5     886   363.6  894.39
   373.5  903.54   389.9  914.96   406.3  924.33   422.7  937.95     433  943.07
#Mann= 3 ,-1,0
       0      .1       0  230.42    .045       0  260.53      .1       0
Bank Sta=230.42,260.53
XS Rating Curve= 0 ,0
Exp/Cntr(USF)=0,0
Exp/Cntr=0.3,0.1

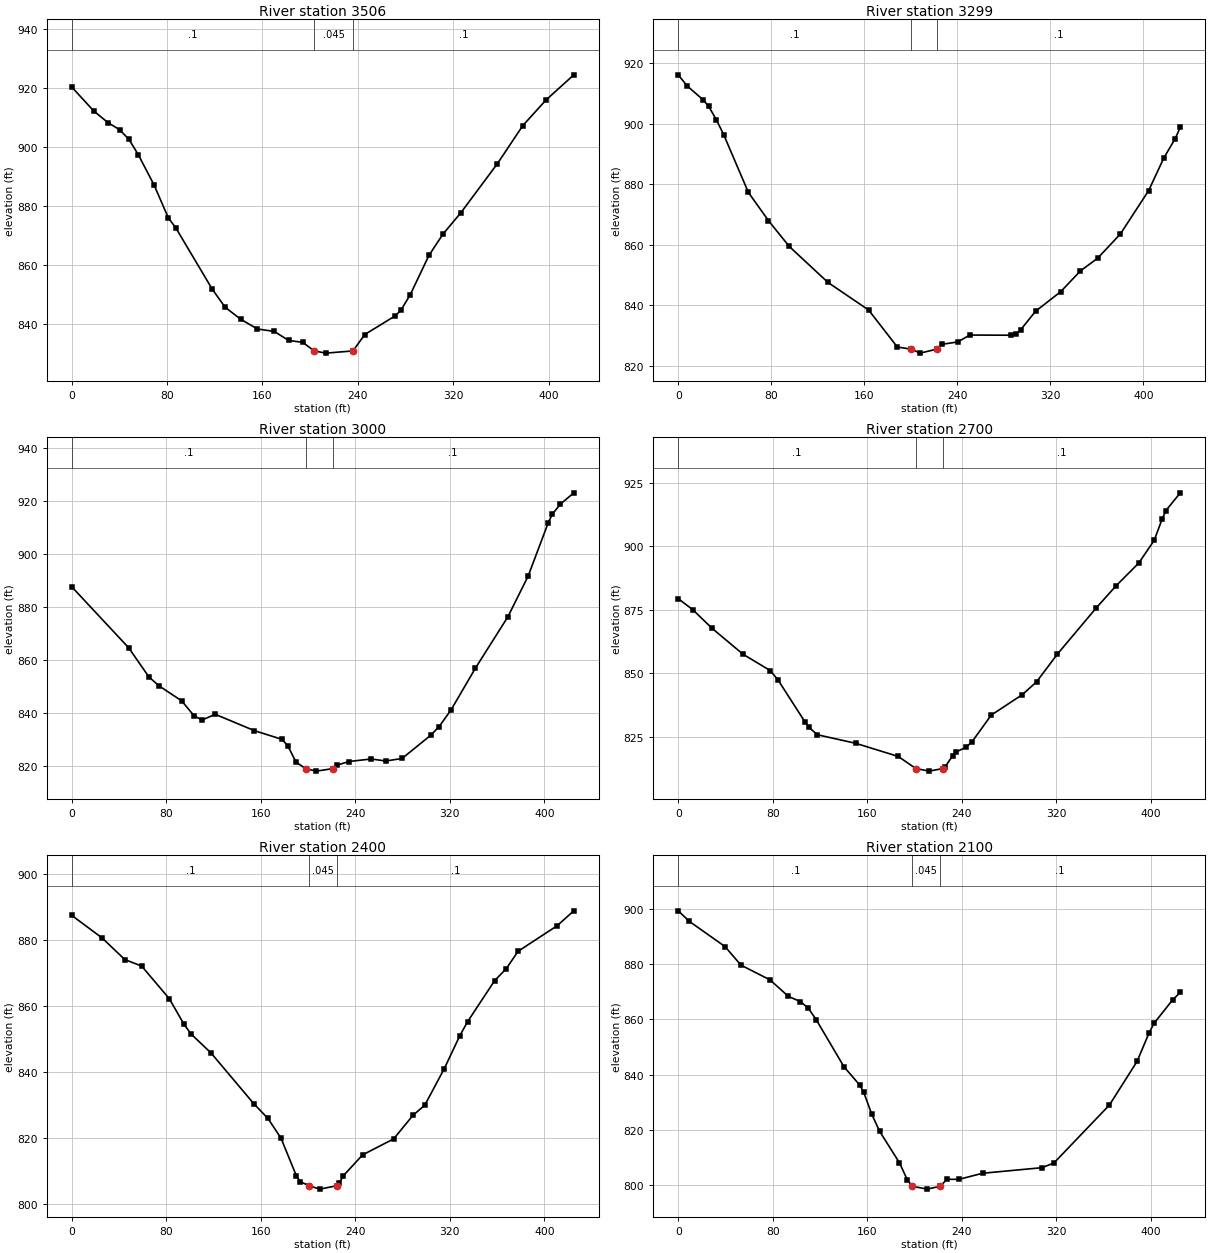
Type RM Length L Ch R = 1 ,3506    ,202.2,207.1,209
XS GIS Cut Line= 2
 1657675.0711569542548.3849746931657442.76654328542899.674878221
#Sta/Elev= 30
       0   920.4    18.5  912.26    30.3  908.36    40.1  905.94      48  902.65
    55.8  897.46    69.1  887.14      81  876.03    87.2  872.68   117.9   851.8
   128.6  845.73   141.6  841.66   155.8  838.33   169.9   837.5   181.9  834.44
   193.7   833.8  203.39830.8893   213.2  830.14  235.91830.8884   245.8  836.45
   271.4   842.8   276.1  844.66     284  850.01   299.7  863.34   311.5  870.57
   326.3   877.7   357.1  894.43   378.4  907.34     398  916.07   421.2  924.55
#Mann= 3 ,-1,0
       0      .1       0  203.39    .045       0  235.91      .1       0
Bank Sta=203.39,235.91
XS Rating Curve= 0 ,0
Exp/Cntr(USF)=0,0
Exp/Cntr=0.3,0.1

Type RM Length L Ch R = 1 ,3299    ,305.2,298.5,295.3
XS GIS Cut Line= 6
1657533.17791176   542444.6214451657478.38865125542514.237775594
1657428.77260876542572.4079348441657354.76357043542641.891719759
1657307.24988592542701.4769024251657258.45208326542775.793682918
#Sta/Elev= 30
       0  916.12     7.6  912.48    21.5  907.83    26.2  905.69    32.7  901.35
    39.1  896.36    60.3  877.31    77.6  867.98    95.5  859.45   128.8  847.57
   163.7  838.48   188.4  826.26  200.41825.5568     208  824.25  222.15825.5571
   226.7  827.16   240.3  827.94   250.7  830.22   286.3  830.16   290.5  830.57
   294.6  832.03   307.2  838.06   328.9  844.55   345.8  851.39   360.6  855.58
   380.2  863.59   404.5  877.93   417.5  888.66   427.3  895.06   431.7  898.83
#Mann= 3 ,-1,0
       0      .1       0  200.41    .045       0  222.15      .1       0
Bank Sta=200.41,222.15
XS Rating Curve= 0 ,0
Exp/Cntr(USF)=0,0
Exp/Cntr=0.3,0.1

Type RM Length L Ch R = 1 ,3000    ,303,299.9,297
XS GIS Cut Line= 6
1657182.82100092542303.1778302491657155.43424468542386.281338587
1657131.95988217542457.5131515121657100.66106026542552.488683343
1657077.18669775542623.7201681731657051.87834942542707.509042591
#Sta/Elev= 30
       0  887.64    48.1  864.69    65.4  853.61    73.9  850.29      93  844.66
   103.4  839.08   110.3  837.41   121.4  839.58   154.6  833.41     178  830.12
   182.9  827.65   189.8  821.58  197.86819.0808     207  818.15  220.77  819.08
   224.8  820.44   234.7  821.78   253.4  822.73   265.8  821.97   279.6  822.92
   303.8  831.66   310.9  834.92     321  841.19   341.7  856.99   369.1  876.29
   386.3  891.67   403.4  911.89   406.8  915.04   413.7  918.87     425  923.08
#Mann= 3 ,-1,0
       0      .1       0  197.86    .045       0  220.77      .1       0
Bank Sta=197.86,220.77
XS Rating Curve= 0 ,0
Exp/Cntr(USF)=0,0
Exp/Cntr=0.3,0.1

Type RM Length L Ch R = 1 ,2700    ,299.5,300.1,300.4
XS GIS Cut Line= 6
1656844.05494617542287.4698564261656840.48605567542374.891597584
1656837.43061559542449.8258309221656833.60089885542549.752796426
1656830.66947426542624.6991688461656827.16521618542712.134361416
#Sta/Elev= 30
       0  879.39    12.2  875.08    28.6  867.74    54.9   857.5    77.9   851.1
    84.5  847.37   107.4  830.82   110.7  828.77   117.7  825.86   150.1   822.5
   186.2  817.32  201.13812.5598   212.5  811.54  223.95812.5608   225.6  813.02
   232.2  817.54   235.5  819.15   243.3  820.85   248.6  823.04     265  833.59
   291.3  841.64   303.3  846.65   320.9  857.55   353.8  875.73   370.6  884.44
   389.8  893.38   402.9  902.34   409.5  910.57   412.8  914.04     425  921.02
#Mann= 3 ,-1,0
       0      .1       0  201.13    .045       0  223.95      .1       0
Bank Sta=201.13,223.95
XS Rating Curve= 0 ,0
Exp/Cntr(USF)=0,0
Exp/Cntr=0.3,0.1

Type RM Length L Ch R = 1 ,2400    ,298.3,300.1,301.4
XS GIS Cut Line= 6
1656554.92822784542251.088367507 1656548.2697766542338.337864921
1656542.52011618542413.1195394991656534.81015784542512.822096005
1656529.13201959542587.6044267571656522.51326643542674.850315258
#Sta/Elev= 30
       0  887.42    25.7   880.6    44.9  874.07    59.2  872.08    82.6  862.21
    94.8  854.59   100.9  851.57   117.8  845.84     154   830.5   166.1  825.99
   177.1  820.04   190.2  808.58   193.5  806.86   200.7 805.665     210  804.62
  224.42805.6628   226.4  806.35   229.7   808.6   246.2  814.99   272.5  819.82
   288.9  826.98   298.8     830   315.3  841.05   328.4  850.98     335  855.25
     358  867.72   367.9  871.36   377.8  876.57   410.7  884.26     425  888.81
#Mann= 3 ,-1,0
       0      .1       0   200.7    .045       0  224.42      .1       0
Bank Sta=200.7,224.42
XS Rating Curve= 0 ,0
Exp/Cntr(USF)=0,0
Exp/Cntr=0.3,0.1

Type RM Length L Ch R = 1 ,2100    ,300.7,300,299.3
XS GIS Cut Line= 6
1656285.94681042542214.9647520931656267.79035068542300.560381427
1656252.22771776542373.9280168411656231.47710308542471.751312003
1656215.91414209542545.1189474171656197.75702618542630.714248672
#Sta/Elev= 30
       0  899.39     9.5  895.53    39.6  886.44    53.1   879.7    77.6  874.38
    93.3  868.36   103.4  866.49   110.1   864.1   116.8  859.93   140.3  842.85
   153.7   836.2     157  833.61   163.7  825.79   170.4  819.51   187.2  808.09
   193.9  801.91  198.11 799.538   210.7   798.5  221.68799.5364   227.5  802.08
   237.5  802.04   257.6  804.25     308  806.28     318  807.97     365     829
   388.4  844.81   398.5  855.08   402.7  858.58   418.6  867.16     425  869.81
#Mann= 3 ,-1,0
       0      .1       0  198.11    .045       0  221.68      .1       0
Bank Sta=198.11,221.68
XS Rating Curve= 0 ,0
Exp/Cntr(USF)=0,0
Exp/Cntr=0.3,0.1

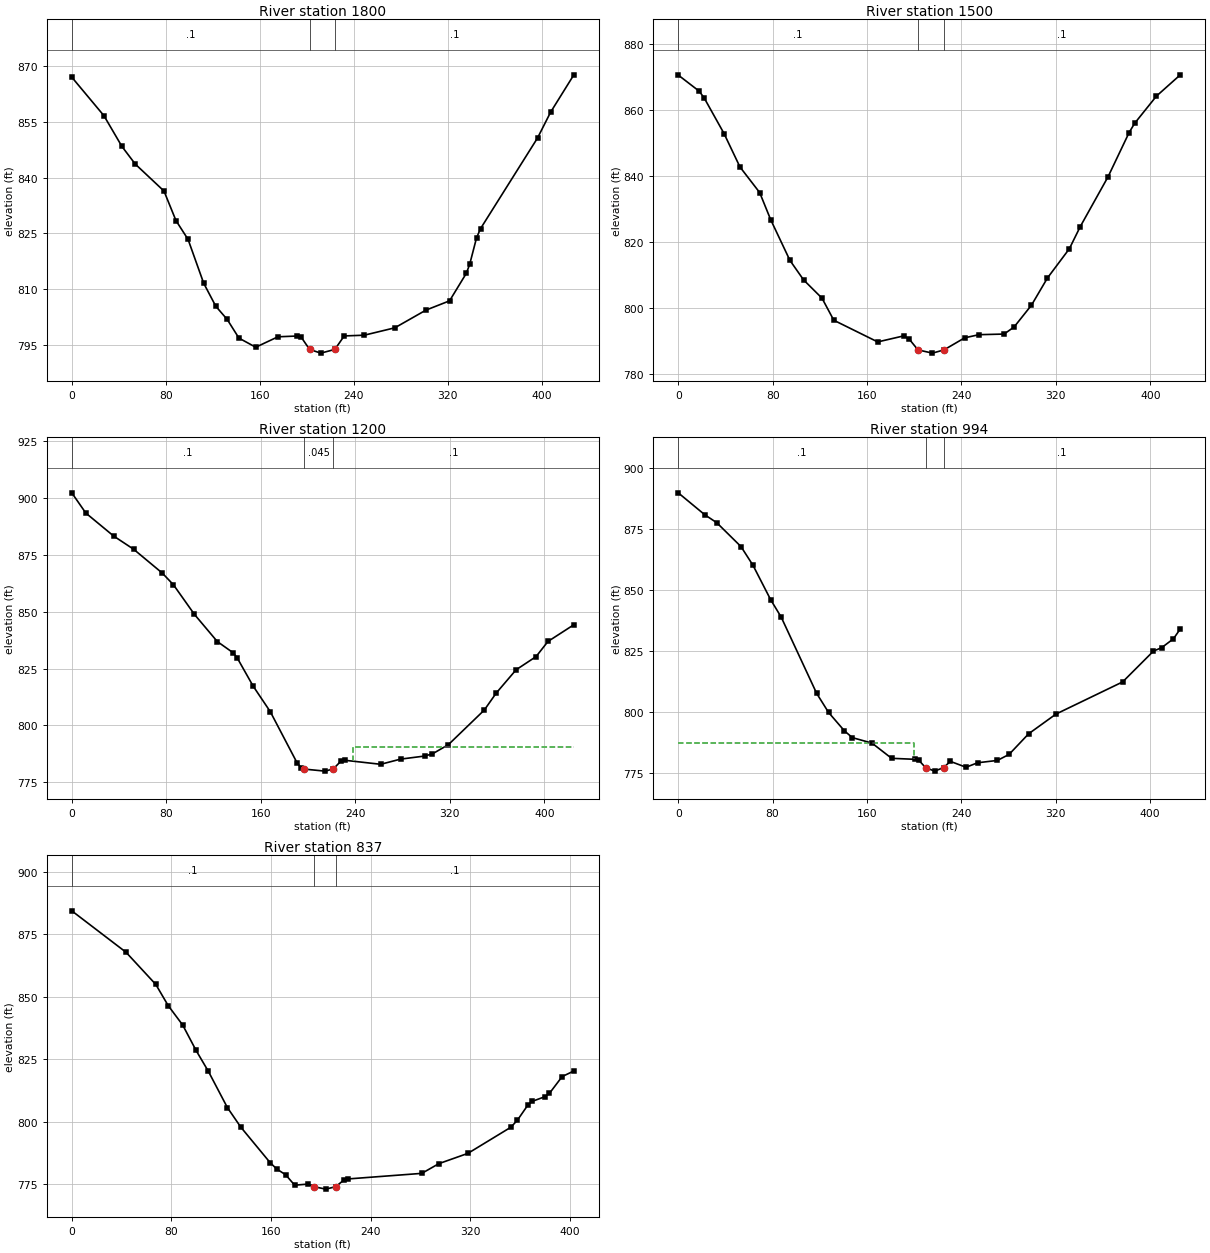
Type RM Length L Ch R = 1 ,1800    ,290.4,299.6,304.5
XS GIS Cut Line= 6
1655997.38734818542166.9796118441655966.43596651542251.336726591
1655953.45010009542325.2355289161655938.97014217 542424.18152526
1655928.11025576542498.3910225031655915.44033359542584.968933344
#Sta/Elev= 30
       0  867.06    27.4  856.67    42.7  848.39      54  843.66    78.5  836.38
    88.7  828.42      99  823.35   112.3  811.54   122.6  805.34   132.3  801.79
   142.3  796.76   156.6   794.3   175.5  797.11   192.1  797.32   195.4  796.96
  202.46793.7081     212  792.71  223.96 793.708   231.9  797.34     249  797.54
     275  799.53   301.5   804.3   321.6   806.8   335.8  814.18   338.7  816.59
   344.6  823.81     348  826.27   396.5  850.68   407.6  857.62   427.4  867.69
#Mann= 3 ,-1,0
       0      .1       0  202.46    .045       0  223.96      .1       0
Bank Sta=202.46,223.96
XS Rating Curve= 0 ,0
Exp/Cntr(USF)=0,0
Exp/Cntr=0.3,0.1

Type RM Length L Ch R = 1 ,1500    ,307.3,300.4,294.2
XS GIS Cut Line= 6
1655885.26618133542051.7337793411655818.74630126542108.957418174
1655762.21065317542158.4881590011655690.87090084 542228.56971176
1655637.83754234542281.6024140861655575.96627501542343.474665672
#Sta/Elev= 30
       0  870.49    17.7  865.63      22  863.55    38.8   852.8    52.3  842.68
      69  834.94    78.3  826.76    94.6  814.44   106.2  808.52   121.8  802.99
   131.8  796.31     169  789.75   191.2  791.59   195.9  790.51  203.13787.3375
   215.4  786.36  225.17787.3375   242.7  790.99   254.8  791.94   276.1  792.13
   284.6  794.28   299.3  800.87   312.8  809.08   331.4  817.95   340.6  824.62
   364.2  839.73     382  853.08   386.7  855.89   405.2  864.13   425.4  870.56
#Mann= 3 ,-1,0
       0      .1       0  203.13    .045       0  225.17      .1       0
Bank Sta=203.13,225.17
XS Rating Curve= 0 ,0
Exp/Cntr(USF)=0,0
Exp/Cntr=0.3,0.1

Type RM Length L Ch R = 1 ,1200    ,207.8,205.6,204.6
XS GIS Cut Line= 6
 1655519.4470311 541841.915957511655499.18001126541927.036522165
1655481.80799876541999.997006178 1655458.6459716542097.277651504
1655441.27428718542170.2378074231655421.00759542542255.358372092
#Sta/Elev= 30
       0  902.32    11.9  893.42    35.5  883.28    52.4  877.48    76.6  867.01
    86.1  861.83   103.8  848.84   123.2  836.87   136.7  831.89   140.1  829.62
   153.5  817.28     168  806.04   190.6   783.6     194  781.39  196.49780.7529
   214.3  779.84  221.26  780.75   227.7  784.16   231.1  784.62   261.5  782.85
   278.3  785.12   298.6  786.47   305.3  787.44   318.8  791.48   349.2  806.72
   359.3   814.2   376.1  824.43     393  830.24   403.1  836.91     425  844.26
#Mann= 3 ,-1,0
       0      .1       0  196.49    .045       0  221.26      .1       0
#XS Ineff= 2 , 0
                          237.91          790.39
Permanent Ineff=
       F       F
Bank Sta=196.49,221.26
XS Rating Curve= 0 ,0
Exp/Cntr(USF)=0,0
Exp/Cntr=0.3,0.1

Type RM Length L Ch R = 1 ,994     ,155.6,157.8,160.1
XS GIS Cut Line= 6
1655313.98698544541822.0808772211655289.66354328541906.765747226
1655274.66586986541980.3407313141655259.45986352 542079.17780397
1655248.05568686542153.3056084731655234.75026728542239.788375146
#Sta/Elev= 30
       0   889.8    22.4  880.86    32.7  877.55    53.2  867.79    63.4  860.11
    78.3  846.09    87.3   838.9   117.4  807.64   127.5  799.85   140.9  792.34
   147.6  789.56   164.3  787.31   180.9  781.09   200.8  780.67   204.1  780.23
  209.67777.2953   217.4  775.84  225.04777.2952   230.7  779.84     244  777.43
   253.9  779.27   270.6  780.22   280.5  782.68   297.1  791.13   320.3  799.21
   376.8  812.37   402.9  824.98   409.9   826.4   419.9  830.04   425.7  834.09
#Mann= 3 ,-1,0
       0      .1       0  209.67    .045       0  225.04      .1       0
#XS Ineff= 2 , 0
             200  787.18
Permanent Ineff=
       F       F
Bank Sta=209.67,225.04
XS Rating Curve= 0 ,0
Exp/Cntr(USF)=0,0
Exp/Cntr=0.3,0.1

Type RM Length L Ch R = 1 ,837     ,208.2,206.6,203.6
XS GIS Cut Line= 3
1655197.50772469541811.6436550051655098.87794293 542030.93753146
1655053.76006404542187.276228072
#Sta/Elev= 30
       0  884.46    43.6  867.86    67.5  854.98    77.4  846.54    89.1  838.73
    99.8   828.6   109.7  820.21     125  805.68   135.8  797.84   159.3  783.66
   164.6  781.12   171.8  778.79     179  774.64   189.8  775.08  194.51774.0322
     204  773.06  211.91774.0295   218.6  776.73   222.2  777.15   281.1  779.37
   294.8  783.26   318.1  787.37   352.6  797.83   357.9  800.67   366.5  806.87
   369.9  808.22   380.2   810.1   383.6   811.4   393.8  818.11   403.2  820.35
#Mann= 3 ,-1,0
       0      .1       0  194.51    .045       0  211.91      .1       0
Bank Sta=194.51,211.91
XS Rating Curve= 0 ,0
Exp/Cntr(USF)=0,0
Exp/Cntr=0.3,0.1