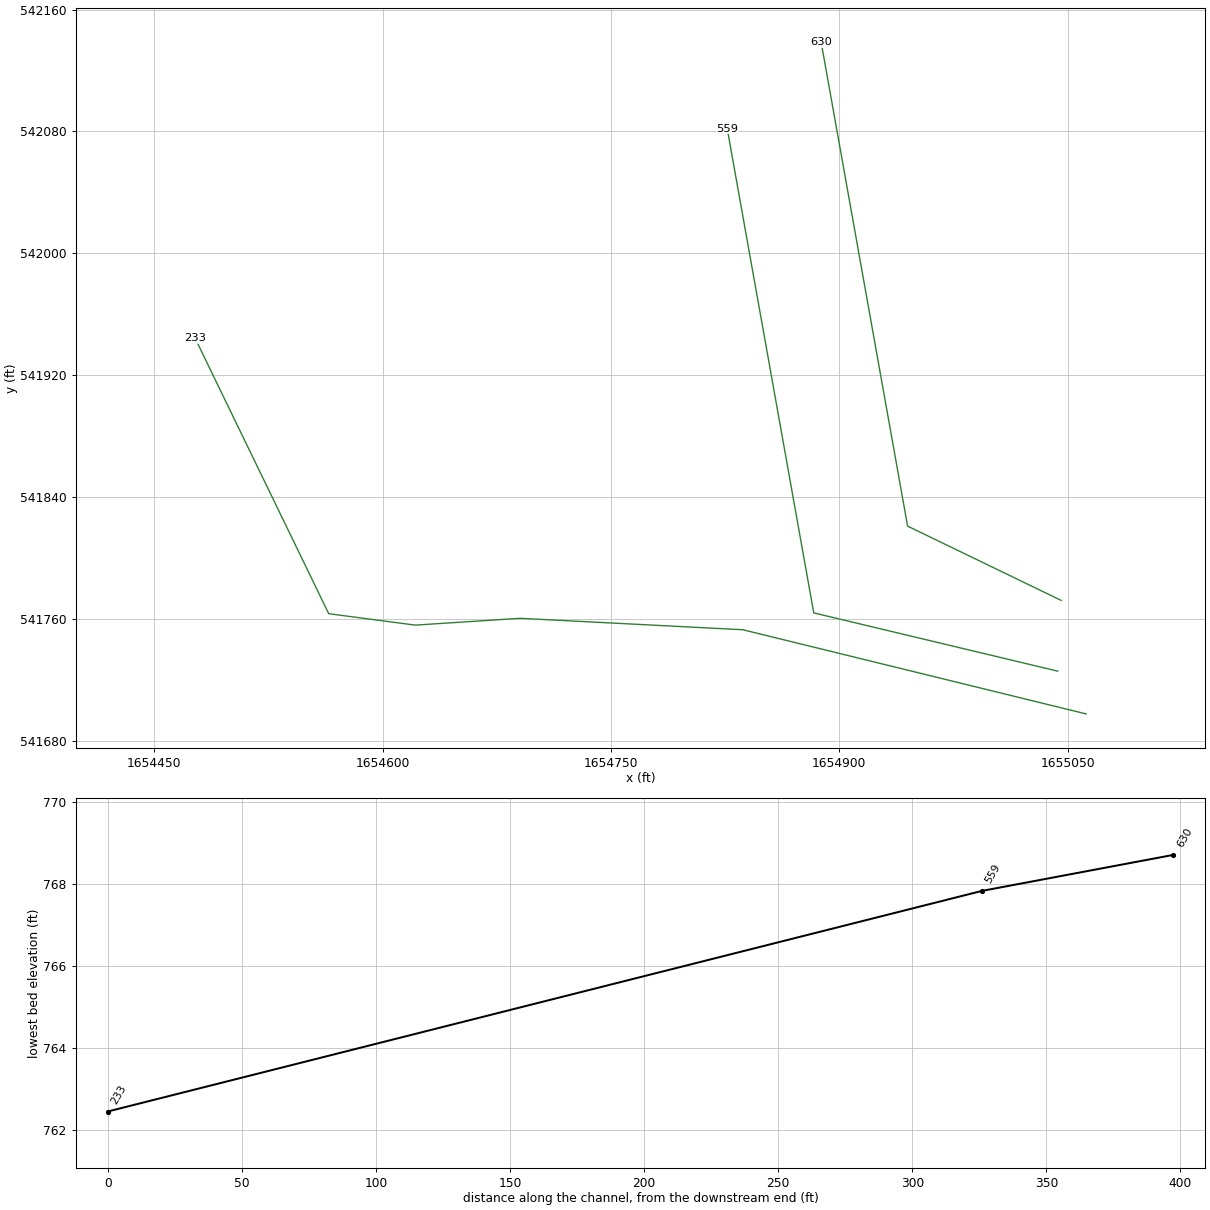
HEC-RAS study BruceRn.prj: BruceRn

--- BruceRn.g01 (geometry) --- (continued)

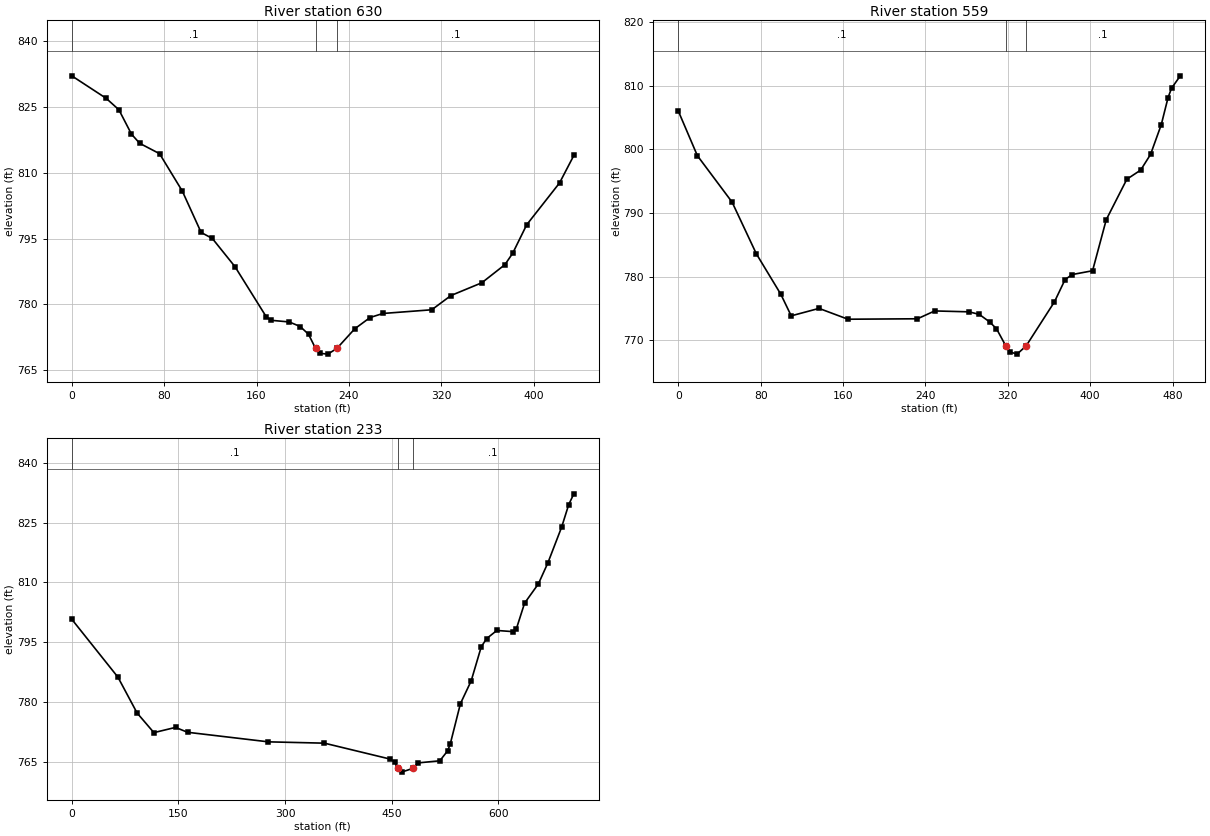
Type RM Length L Ch R = 1 ,630     ,71.3,71.4,71.5
XS GIS Cut Line= 3
1655045.72626774541772.2707106141654944.86453086 541821.01135079
1654888.04967184542138.698172346
#Sta/Elev= 30
       0  832.02    29.8   826.9    40.8   824.3    51.7  818.75    58.8  816.67
      76  814.31    95.7   805.8     112  796.39   121.7  795.02   141.3  788.61
   168.3  777.24   172.4  776.41   188.3  776.03   197.8  774.99     205  773.22
  211.09769.9998     215  768.89   221.7  768.71  229.52770.0007     245  774.47
   258.3  777.04   269.4  777.96   311.7   778.8   328.3  782.04     355  784.94
     375  789.06   381.7  791.63   393.9  798.15   422.3  807.65   434.7  813.91
#Mann= 3 ,-1,0
       0      .1       0  211.09    .045       0  229.52      .1       0
Bank Sta=211.09,229.52
XS Rating Curve= 0 ,0
Exp/Cntr(USF)=0,0
Exp/Cntr=0.3,0.1

Type RM Length L Ch R = 1 ,559     ,312.3,326,336.3
XS GIS Cut Line= 3
 1655043.5220521541725.8182880391654883.20264536541764.066398242
1654826.38778635542081.753219797
#Sta/Elev= 30
       0  806.02    18.6  798.98    52.3  791.69    75.9  783.56    99.6  777.23
   109.7  773.84   136.7  775.01   164.8  773.31   232.3  773.38     249  774.61
   282.3  774.47   292.3  774.07   302.3  772.89     309  771.82  318.07769.1203
   322.3  768.17     329  767.83   337.8769.1193   365.3  776.04   375.6  779.53
   382.4  780.32   402.3  780.92   415.6  788.94   435.6  795.29     449  796.72
   458.6  799.18     469  803.85   475.6   808.1     479  809.58   487.5  811.52
#Mann= 3 ,-1,0
       0      .1       0  318.07    .045       0   337.8      .1       0
Bank Sta=318.07,337.8
XS Rating Curve= 0 ,0
Exp/Cntr(USF)=0,0
Exp/Cntr=0.3,0.1

Type RM Length L Ch R = 1 ,233     ,,,
XS GIS Cut Line= 6
1655062.17025728541697.7521120281654836.62339873541752.999486789
1654690.27605696541760.4993915261654621.39922758541756.036647006
1654564.57906024541763.532460195 1654476.7539065541944.384584591
#Sta/Elev= 30
       0  800.76    64.9  786.25    91.9  777.25   115.5  772.34   145.9  773.65
   162.8  772.43   276.6  770.03   355.3   769.7   447.3  765.73   453.9     765
   458.8763.3563   463.8  762.44  479.33763.3558   487.4  764.76   517.6  765.28
   528.5  767.75   532.2  769.43   546.6  779.61   561.7  785.31   575.9  793.87
   583.5  795.92   597.8  797.95   620.4  797.66   625.3  798.38   636.8  804.79
   656.2  809.62   669.5  814.86     689  823.89   698.9  829.51   706.1   832.2
#Mann= 3 ,-1,0
       0      .1       0   458.8    .045       0  479.33      .1       0
Bank Sta=458.8,479.33
XS Rating Curve= 0 ,0
Exp/Cntr(USF)=0,0
Exp/Cntr=0.3,0.1
LCMann Table=0

Chan Stop Cuts=-1
Use User Specified Reach Order=0
Composite Channel Slope=5